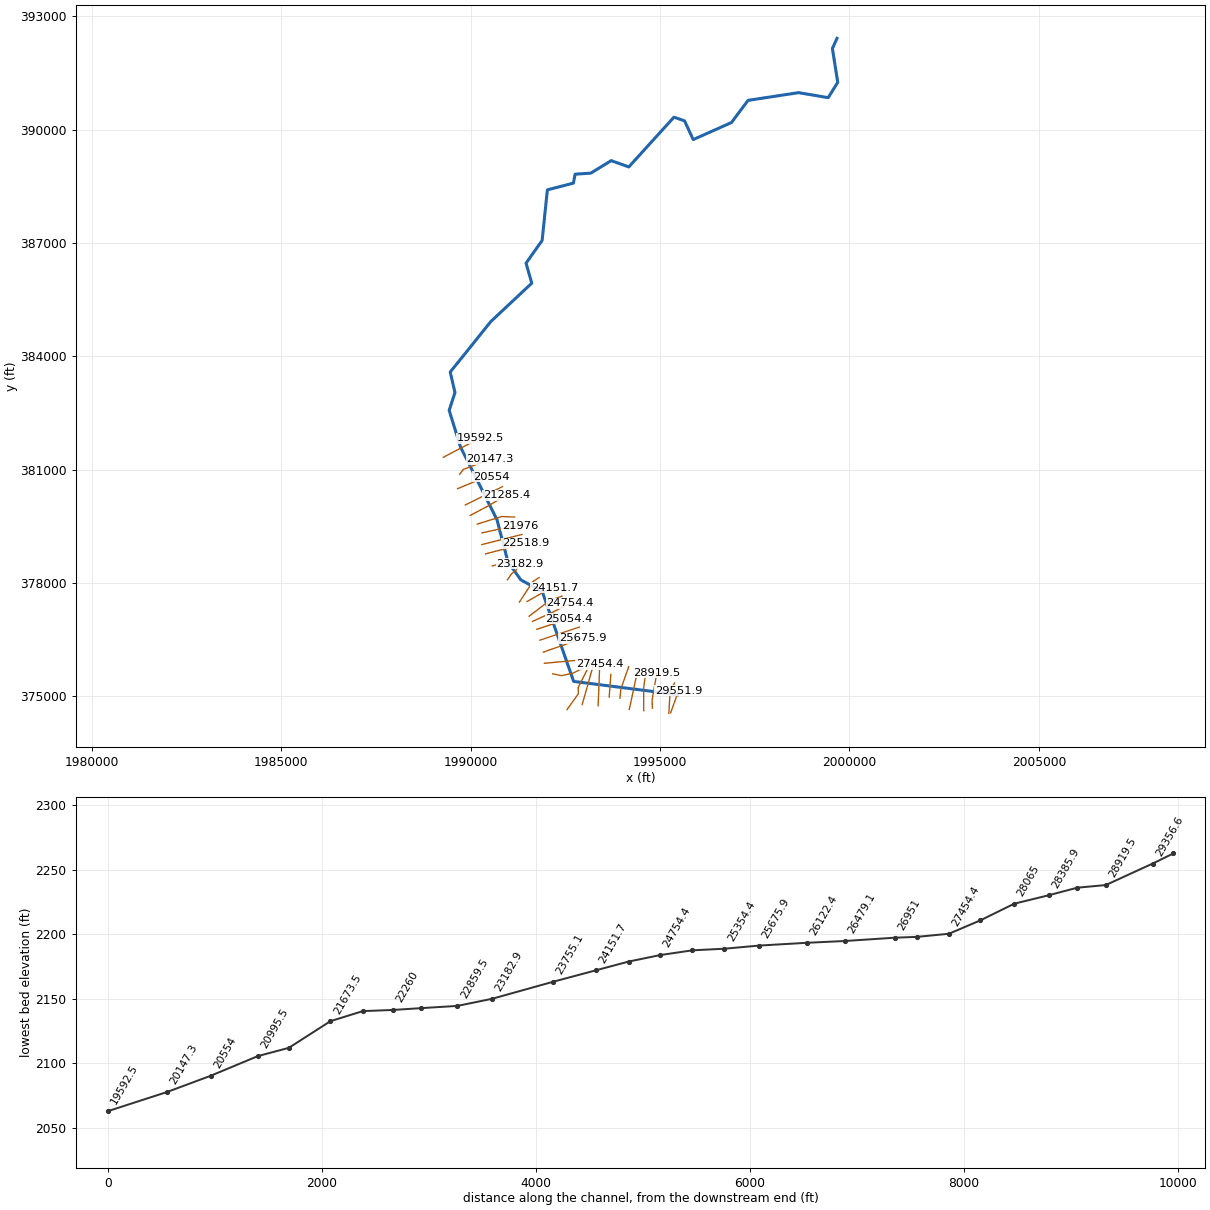
--- BrakensCrk.prj (project) ---

Proj Title=BrakensCrk
Current Plan=p01
Default Exp/Contr=0,0
English Units
Geom File=g01
Flow File=f01
Plan File=p01
BEGIN DESCRIPTION:
END DESCRIPTION:
DSS Export Rating Curves= 0
DSS Export Rating Curve Sorted= 0
DSS Export Volume Flow Curves= 0
DXF OffsetX= 0
DXF OffsetY= 0
DXF ScaleX= 0
DXF ScaleY= 0

--- BrakensCrk.p01 (plan) ---

Plan Title=Floodplain
Program Version=4.00
Geom File=g01
Flow File=f01
K Sum by GR=0
Std Step Tol=0.01
Critical Tol=0.01
Num of Std Step Trials=20
Max Error Tol=0.3
Flow Tol Ratio=0.001
Split Flow NTrial=30
Split Flow Tol=0.02
Split Flow Ratio=0.02
Log Output Level=0
Friction Slope Method=1
Unsteady Friction Slope Method=2
Unsteady Bridges Friction Slope Method=1
Global Log Level=0
CheckData=False
Run HTab=0
Run UNet=0
Run PostProcess=0
UNET Theta=0
UNET Theta Warmup=0
UNET ZTol=0
UNET ZSATol=0
UNET MxIter=0
UNET MaxInSteps=0
UNET DtIC=0
UNET DtMin=0
UNET MaxCRTS=0
UNET WFStab=0
UNET SFStab=0
UNET WFX=0
UNET SFX=0
UNET DSS MLevel=0
UNET DZMax Abort=0
UNET Convert EG Bridges=0
UNET Use Existing IB Tables=0
UNET Froude Limit=0
UNET Froude Power=0
Write IC File=0
Echo Input=False
Echo Output=False
Write Detailed=0

--- BrakensCrk.f01 (steady flow) ---

Flow Title=NFF Regression Equation
Program Version=4.10
Number of Profiles= 1
Profile Names=P100yr
River Rch & RM=BrakensCrk,Main            ,29551.9
721.3016
River Rch & RM=BrakensCrk,Main            ,27454.4
768.8599
River Rch & RM=BrakensCrk,Main            ,25675.9
853.8991
River Rch & RM=BrakensCrk,Main            ,19592.5
1085.312
River Rch & RM=BrakensCrk,Main            ,19354.4
1376.217
River Rch & RM=BrakensCrk,Main            ,17839
1771.212
River Rch & RM=BrakensCrk,Main            ,16564.7
1848.519
River Rch & RM=BrakensCrk,Main            ,8417.4
 2048.13
River Rch & RM=BrakensCrk,Main            ,7953.4
2292.154
River Rch & RM=BrakensCrk,Main            ,1076.5
2749.663
River Rch & RM=BrakensCrk,Main            ,154.4
2755.722
Boundary for River Rch & Prof#=BrakensCrk,Main            , 1
Up Type= 0
Dn Type= 3
Dn Slope=0.002888
DSS Import GetInterval= 0
DSS Import GetPeak= 0
DSS Import FillOption= 0

--- BrakensCrk.g01 (geometry) ---

Geom Title=USGS 3m DEM
Program Version=4.10

River Reach=BrakensCrk      ,Main
Reach XY= 30
     1995468.173       375038.02     1992721.789      375389.132
     1991893.521      377767.186     1991327.548       378077.95
     1990989.007      378550.173     1990699.076      379669.964
     1989737.271      381591.839     1989436.923      382565.798
     1989589.701       383038.02     1989464.253      383580.292
     1990537.618      384919.964     1991616.391      385933.188
     1991466.437      386464.409     1991890.048      387065.797
     1992028.316      388404.806     1992715.558       388583.26
     1992760.582       388820.45     1993173.035      388847.047
     1993712.965      389178.645     1994177.818      389012.155
     1995369.215      390329.687     1995648.729      390232.464
     1995877.896      389735.936     1996886.576      390187.325
     1997324.664      390774.736     1998659.146      390978.992
     1999439.606      390845.943     1999692.132      391251.561
     1999551.057      392148.723     1999673.367      392417.255

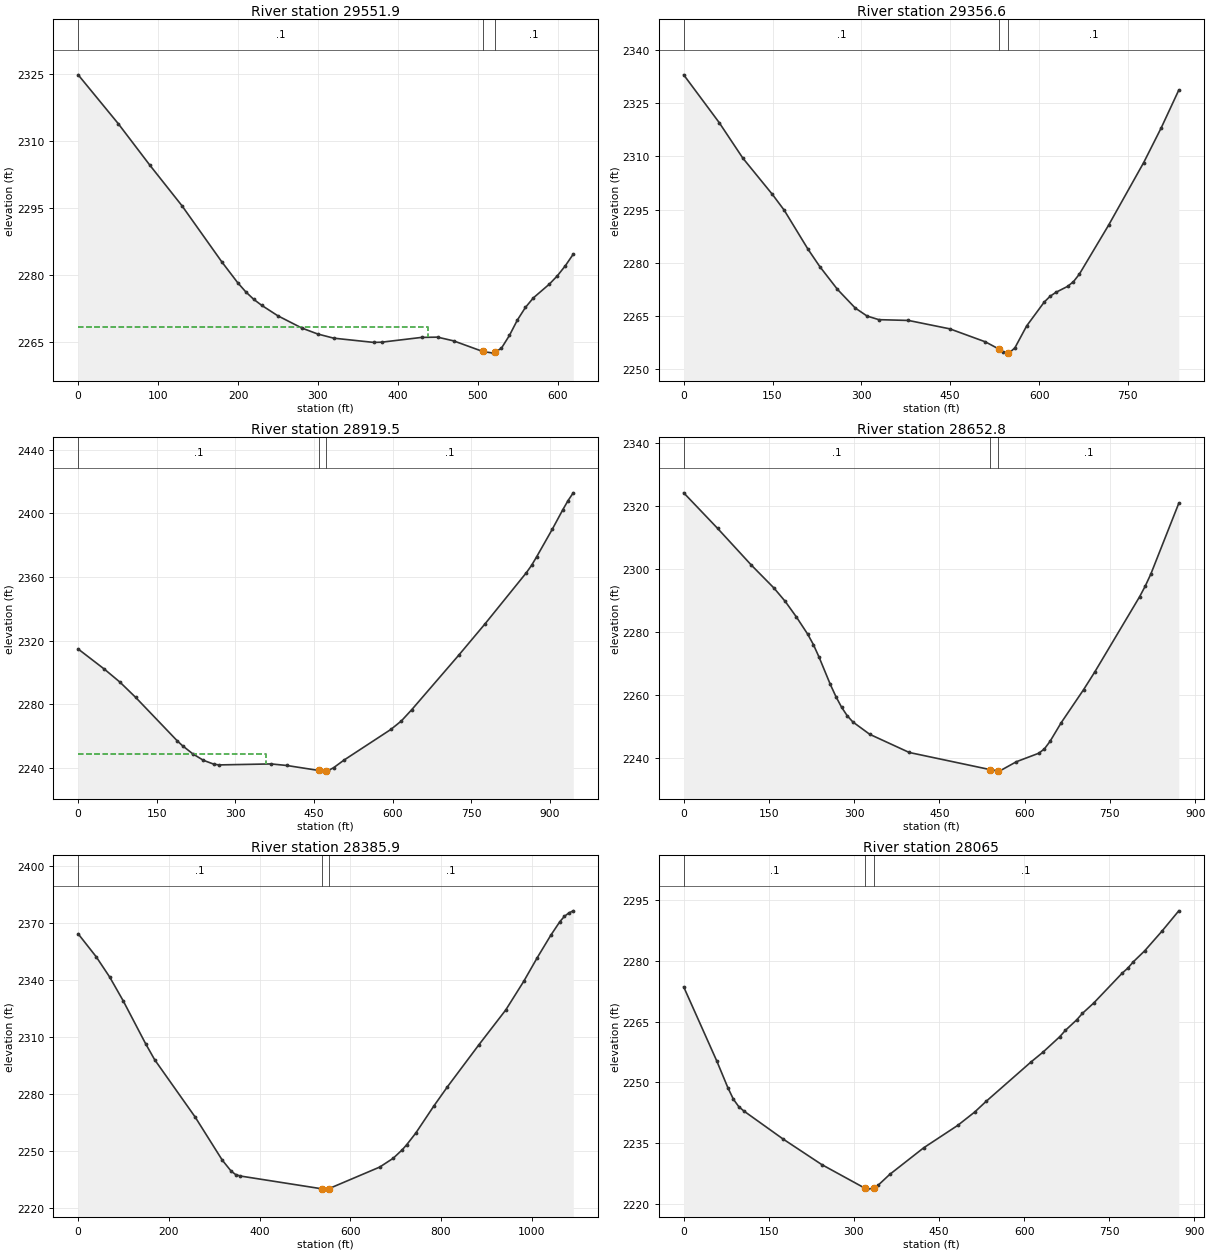
Type RM Length L Ch R = 1 ,29551.9 ,189,195.4,201.9
XS GIS Cut Line= 2
     1995282.737      374558.262     1995491.937      375141.309
#Sta/Elev= 30
       0 2324.82      50 2313.92    89.9 2304.54   129.9  2295.5   179.8 2282.92
   199.8 2278.23   209.8 2276.21   219.8 2274.53   229.8 2273.19   249.8 2270.87
   279.8 2268.13   299.7 2266.79   319.7 2265.86   369.7 2264.91   379.7 2264.96
   429.6 2266.03   449.6 2266.09   469.6 2265.26   506.2 2262.88   519.5 2262.51
   521.2  2262.7   529.5  2263.6   539.5 2266.46   549.5 2269.92   559.5 2272.73
   569.5 2274.88   589.5 2277.96   599.5 2279.82   609.4 2282.05   619.4 2284.67
#Mann= 3 , 0 , 0
       0      .1       0   506.2    .045       0   521.2      .1       0
#XS Ineff= 2 , 0
          438.25 2268.27
Permanent Ineff=
       F       F
Bank Sta=506.2,521.2
XS Rating Curve= 0 ,0
Exp/Cntr=0.3,0.1

Type RM Length L Ch R = 1 ,29356.6 ,439.5,436.9,434.3
XS GIS Cut Line= 3
     1995233.927      374542.196     1995267.236       375110.43
     1995383.463      375350.509
#Sta/Elev= 30
       0 2332.94    59.9  2319.5    99.9 2309.48   149.8 2299.27   169.8 2294.81
   209.7  2283.9   229.7 2278.98   259.6 2272.55   289.6  2267.3   309.6 2265.04
   329.5 2264.02   379.5  2263.8   449.4 2261.43   509.3 2257.78   532.2 2255.75
   539.2 2254.96   547.2 2254.67   549.2  2254.6   559.2 2256.09   579.1 2262.27
   608.7 2268.97   618.6  2270.6   628.5 2271.72   648.2 2273.39   658.1 2274.72
     668 2276.83   717.4 2290.62   776.7 2308.26   806.3 2318.04   835.9 2328.65
#Mann= 3 , 0 , 0
       0      .1       0   532.2    .045       0   547.2      .1       0
Bank Sta=532.2,547.2
XS Rating Curve= 0 ,0
Exp/Cntr=0.3,0.1

Type RM Length L Ch R = 1 ,28919.5 ,262.7,266.7,270.7
XS GIS Cut Line= 3
     1994800.416      374682.232     1994792.668      374901.117
     1994918.575      375615.882
#Sta/Elev= 30
       0 2314.71    49.8 2302.12    79.6 2293.95   109.5  2284.4   189.2 2256.99
   199.1 2253.97     219  2248.8   238.9 2244.83   258.8 2242.38   268.7 2241.91
   368.2 2242.53     398 2241.56   458.8 2238.44   467.6 2238.01   473.8 2238.27
   477.5 2238.42   487.5 2240.17   507.3 2244.94   596.8 2264.21   616.7 2269.51
   636.6 2276.61   726.1 2310.78   775.8 2330.26   855.3 2362.64   865.3 2367.28
   875.2 2372.78     905 2390.08   924.9 2402.22   934.8 2407.91   944.8 2412.81
#Mann= 3 , 0 , 0
       0      .1       0   458.8    .045       0   473.8      .1       0
#XS Ineff= 2 , 0
          358.42 2248.53
Permanent Ineff=
       F       F
Bank Sta=458.8,473.8
XS Rating Curve= 0 ,0
Exp/Cntr=0.3,0.1

Type RM Length L Ch R = 1 ,28652.8 ,271.7,266.8,262
XS GIS Cut Line= 3
     1994571.709      374613.548     1994569.909      375218.791
     1994606.712      375482.227
#Sta/Elev= 30
       0 2324.28    59.5 2313.03   119.1 2301.33   158.8 2294.07   178.6 2289.84
   198.4 2284.86   218.3  2279.4   228.2 2276.13   238.1 2272.18     258 2263.48
   267.9  2259.6   277.8 2256.25   287.7 2253.55   297.7 2251.56   327.4 2247.64
   396.9 2241.88   538.5 2236.47   553.5 2235.99   555.6 2235.96   585.4 2238.94
     625 2241.65   634.8 2243.04   644.6  2245.4   664.4 2251.36   703.8 2261.85
   723.5 2267.47   802.3 2291.32   812.1 2294.66     822  2298.5   871.2 2320.97
#Mann= 3 , 0 , 0
       0      .1       0   538.5    .045       0   553.5      .1       0
Bank Sta=538.5,553.5
XS Rating Curve= 0 ,0
Exp/Cntr=0.3,0.1

Type RM Length L Ch R = 1 ,28385.9 ,323.7,320.9,318.1
XS GIS Cut Line= 3
     1994190.076      374646.818     1994304.478      375180.698
     1994418.406       375714.68
#Sta/Elev= 30
       0 2364.48    39.7 2352.43    69.5 2341.74    99.3 2329.23   148.9 2306.58
   168.8 2298.19   258.1 2268.02   317.7 2245.41   337.5 2239.55   347.4 2237.76
   357.4 2237.01   537.7 2230.26     546  2230.1   552.7 2230.32   665.1 2241.71
   694.9 2246.35   714.8 2250.81   724.7 2253.49   744.6 2259.59   784.2 2273.75
     814 2283.81   883.5 2305.97   943.1 2324.41   982.8 2339.49  1012.6 2351.94
  1042.4 2363.72  1062.2  2370.8  1072.2 2373.61  1082.1 2375.46    1092 2376.59
#Mann= 3 , 0 , 0
       0      .1       0   537.7    .045       0   552.7      .1       0
Bank Sta=537.7,552.7
XS Rating Curve= 0 ,0
Exp/Cntr=0.3,0.1

Type RM Length L Ch R = 1 ,28065   ,311.5,317.3,323.1
XS GIS Cut Line= 3
     1993944.247      374943.732     1993967.491      375185.861
     1994175.117       375780.06
#Sta/Elev= 30
       0 2273.57    58.4 2255.23    77.8 2248.68    87.6 2245.81    97.3 2243.93
     107  2242.8   175.1 2235.98   243.2 2229.67   319.8 2223.79   323.2 2223.59
   334.8 2223.81   343.2 2224.61   363.1 2227.22   423.1 2233.81     483 2239.34
     513 2242.65     533 2245.27   612.9  2255.1   632.9 2257.39   662.9 2261.26
   672.8 2262.83   692.8 2265.43   702.8 2267.02   722.8 2269.59   772.8 2276.95
   782.8  2278.2   792.7 2279.79   812.7  2282.5   842.7 2287.29   872.7 2292.37
#Mann= 3 , 0 , 0
       0      .1       0   319.8    .045       0   334.8      .1       0
Bank Sta=319.8,334.8
XS Rating Curve= 0 ,0
Exp/Cntr=0.3,0.1

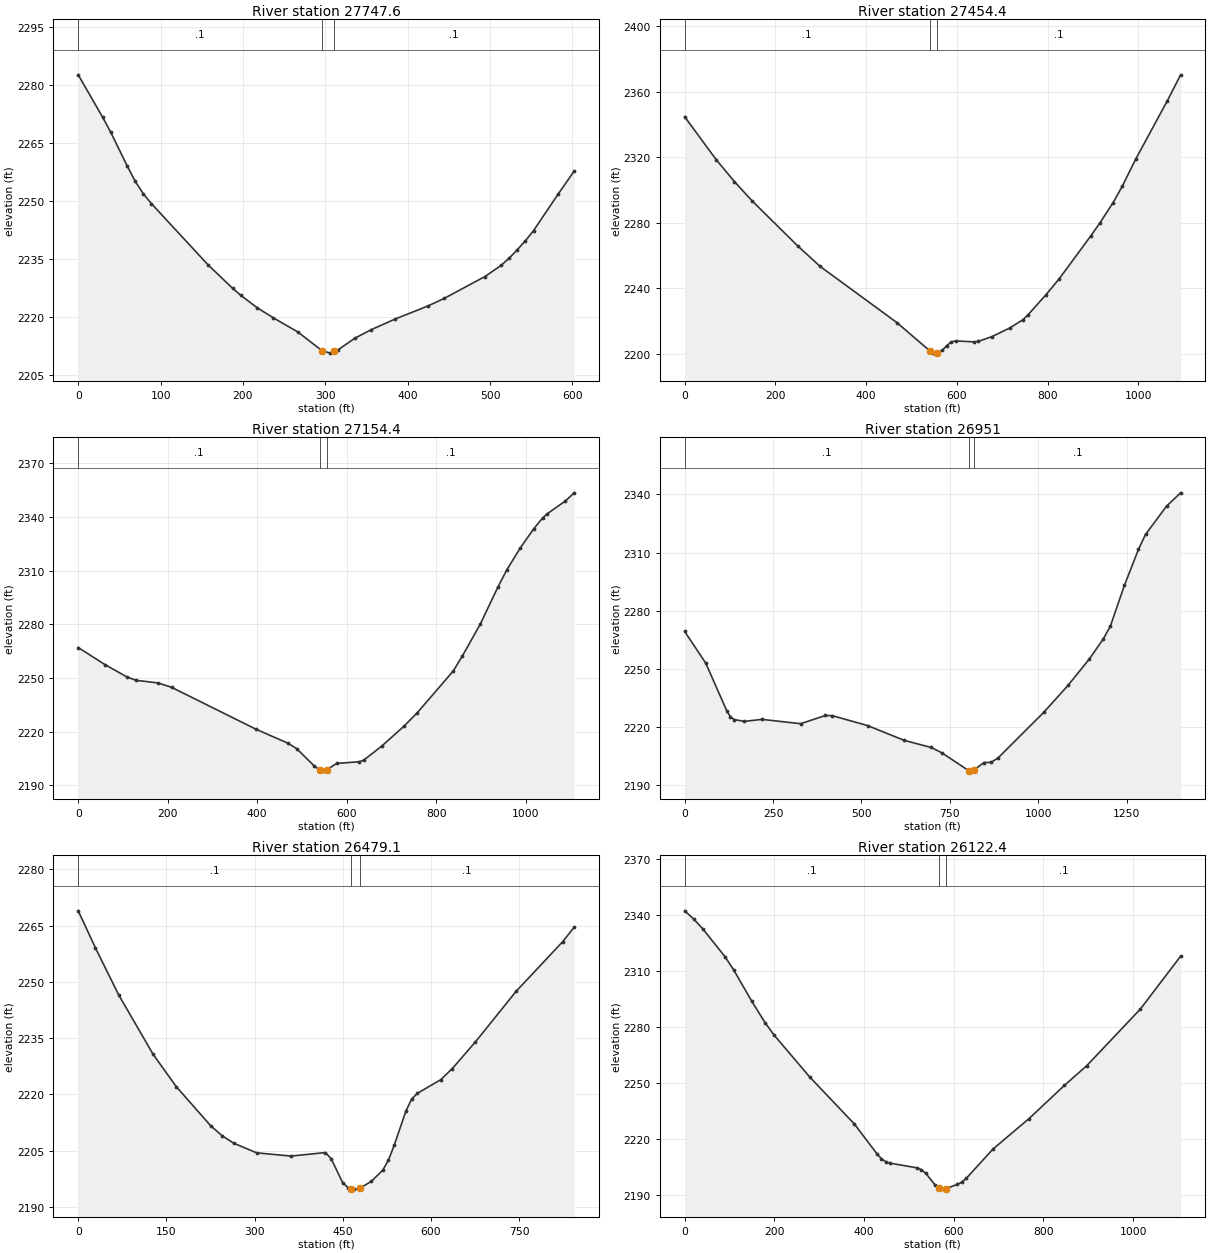
Type RM Length L Ch R = 1 ,27747.6 ,292.3,293.1,294.2
XS GIS Cut Line= 2
     1993659.503      374974.724     1993704.055      375575.205
#Sta/Elev= 30
       0 2282.63    29.6 2271.69    39.5 2267.77    59.2 2259.18    69.1 2255.13
      79 2251.88    88.8 2249.34   157.9 2233.43   187.6  2227.4   197.4 2225.61
   217.2  2222.4   236.9 2219.79   266.5 2216.15   295.7 2211.33     306 2210.66
   310.7 2211.09   315.9 2211.57   335.6 2214.49   355.4 2216.69     385  2219.5
   424.4 2222.83   444.2  2224.8   493.6 2230.44   513.3 2233.33   523.2 2235.22
     533 2237.38   542.9 2239.72   552.8 2242.34   582.4  2251.7   602.1 2257.74
#Mann= 3 , 0 , 0
       0      .1       0   295.7    .045       0   310.7      .1       0
Bank Sta=295.7,310.7
XS Rating Curve= 0 ,0
Exp/Cntr=0.3,0.1

Type RM Length L Ch R = 1 ,27454.4 ,305.2,299.9,294.6
XS GIS Cut Line= 3
     1993367.178       374744.38     1993391.079      375291.492
     1993408.927       375836.68
#Sta/Elev= 30
       0 2344.82    69.7  2318.5   109.5 2305.22   149.4 2293.15   248.9 2265.94
   298.7  2253.3     468 2218.92   540.1 2201.75   547.6 2200.52   555.1 2200.36
   557.6 2200.31   567.5 2201.92   577.4 2204.88   587.3  2207.1   597.2 2207.79
   636.9  2207.2   646.8 2207.49   676.6 2210.33   716.2 2215.61     746 2220.84
   755.9 2223.48   795.6 2235.77   825.3 2245.66   894.8 2271.86   914.6 2279.66
   944.4 2292.36   964.2  2302.2   993.9 2318.79  1063.4 2354.39  1093.1 2370.45
#Mann= 3 , 0 , 0
       0      .1       0   540.1    .045       0   555.1      .1       0
Bank Sta=540.1,555.1
XS Rating Curve= 0 ,0
Exp/Cntr=0.3,0.1

Type RM Length L Ch R = 1 ,27154.4 ,208.5,203.4,198.1
XS GIS Cut Line= 3
     1992946.509      374775.239     1993096.474      375301.933
     1993245.634      375842.307
#Sta/Elev= 30
       0 2267.01    59.7 2257.47   109.5 2250.48   129.4 2248.68   179.2 2247.18
   209.1  2244.7   398.3  2221.2     468 2213.58   487.9 2210.52   527.7 2200.72
   540.1 2198.38   547.6 2197.89   555.1  2198.6   577.7 2202.21   627.7 2203.13
   637.7 2203.98   677.8 2211.79   727.8    2223   757.8  2230.6   837.9 2253.84
     858  2262.1     898  2279.9     938 2300.91     958 2310.58   988.1  2322.8
  1018.1 2333.49  1038.1 2339.58  1048.2 2341.84  1088.2 2348.87  1108.2 2353.53
#Mann= 3 , 0 , 0
       0      .1       0   540.1    .045       0   555.1      .1       0
Bank Sta=540.1,555.1
XS Rating Curve= 0 ,0
Exp/Cntr=0.3,0.1

Type RM Length L Ch R = 1 ,26951   ,488.2,469.8,446.2
XS GIS Cut Line= 4
     1992545.709       374639.94     1992846.272      375060.942
     1992842.721      375231.381     1993165.441      375869.837
#Sta/Elev= 30
       0 2269.31    59.7 2252.94   119.4 2228.24   129.3 2225.36   139.3 2223.89
   169.1 2222.93   218.8 2223.95   328.3 2221.74   397.9 2225.96   417.8 2225.87
   517.3 2220.77   621.5 2213.11   697.7 2209.46   727.5 2206.72     804 2197.47
     807 2197.27     819 2197.95   846.7 2201.69   866.6  2201.8   886.5 2204.06
  1015.6 2227.54  1085.2 2241.63  1144.8 2255.09  1184.6 2265.51  1204.4 2272.08
  1244.2 2293.13  1283.9 2311.67  1303.8 2319.33  1363.4 2333.96  1403.1  2340.8
#Mann= 3 , 0 , 0
       0      .1       0     804    .045       0     819      .1       0
Bank Sta=804,819
XS Rating Curve= 0 ,0
Exp/Cntr=0.3,0.1

Type RM Length L Ch R = 1 ,26479.1 ,357.4,355.7,357.9
XS GIS Cut Line= 4
     1992171.216      375590.055     1992401.393      375541.164
     1992705.837      375609.426     1992973.148       375737.27
#Sta/Elev= 30
       0 2268.95    29.4 2259.03    68.6 2246.59   127.5 2230.64   166.7 2222.06
   225.5 2211.58   245.1 2208.91   264.6 2206.95   303.6 2204.38   362.1 2203.52
   420.6 2204.46   430.3 2202.81   449.8 2196.44   459.6    2195   464.2 2194.86
   469.3  2194.7   479.2 2194.97   498.6 2196.76   518.1 2199.78   527.8 2202.46
   537.6 2206.44   557.2 2215.44   567.1 2218.71     577 2220.27   616.4 2223.87
   636.2 2226.84   675.7 2233.99   744.8 2247.46   823.9 2260.69   843.6 2264.57
#Mann= 3 , 0 , 0
       0      .1       0   464.2    .045       0   479.2      .1       0
Bank Sta=464.2,479.2
XS Rating Curve= 0 ,0
Exp/Cntr=0.3,0.1

Type RM Length L Ch R = 1 ,26122.4 ,440.4,446.8,453.3
XS GIS Cut Line= 2
     1991951.363      375868.746     1993052.566       375970.44
#Sta/Elev= 30
       0 2342.04    19.9  2337.7    39.8 2332.59    89.7 2317.59   109.6 2310.34
   149.4 2293.82   179.3 2282.25   199.3 2275.68     279 2253.18   378.6 2228.08
   428.4 2212.29   438.4 2209.62   448.3 2207.96   458.3 2207.17   518.1  2204.7
     528  2203.7     538 2201.69   557.9 2195.64   568.1 2193.73   577.8 2193.31
   583.1 2193.61   607.7 2195.81   617.7 2197.05   627.7 2199.01   687.4 2214.71
   767.2 2230.86   846.8 2248.75   896.7  2259.3  1016.2 2289.57  1105.9 2317.78
#Mann= 3 , 0 , 0
       0      .1       0   568.1    .045       0   583.1      .1       0
Bank Sta=568.1,583.1
XS Rating Curve= 0 ,0
Exp/Cntr=0.3,0.1

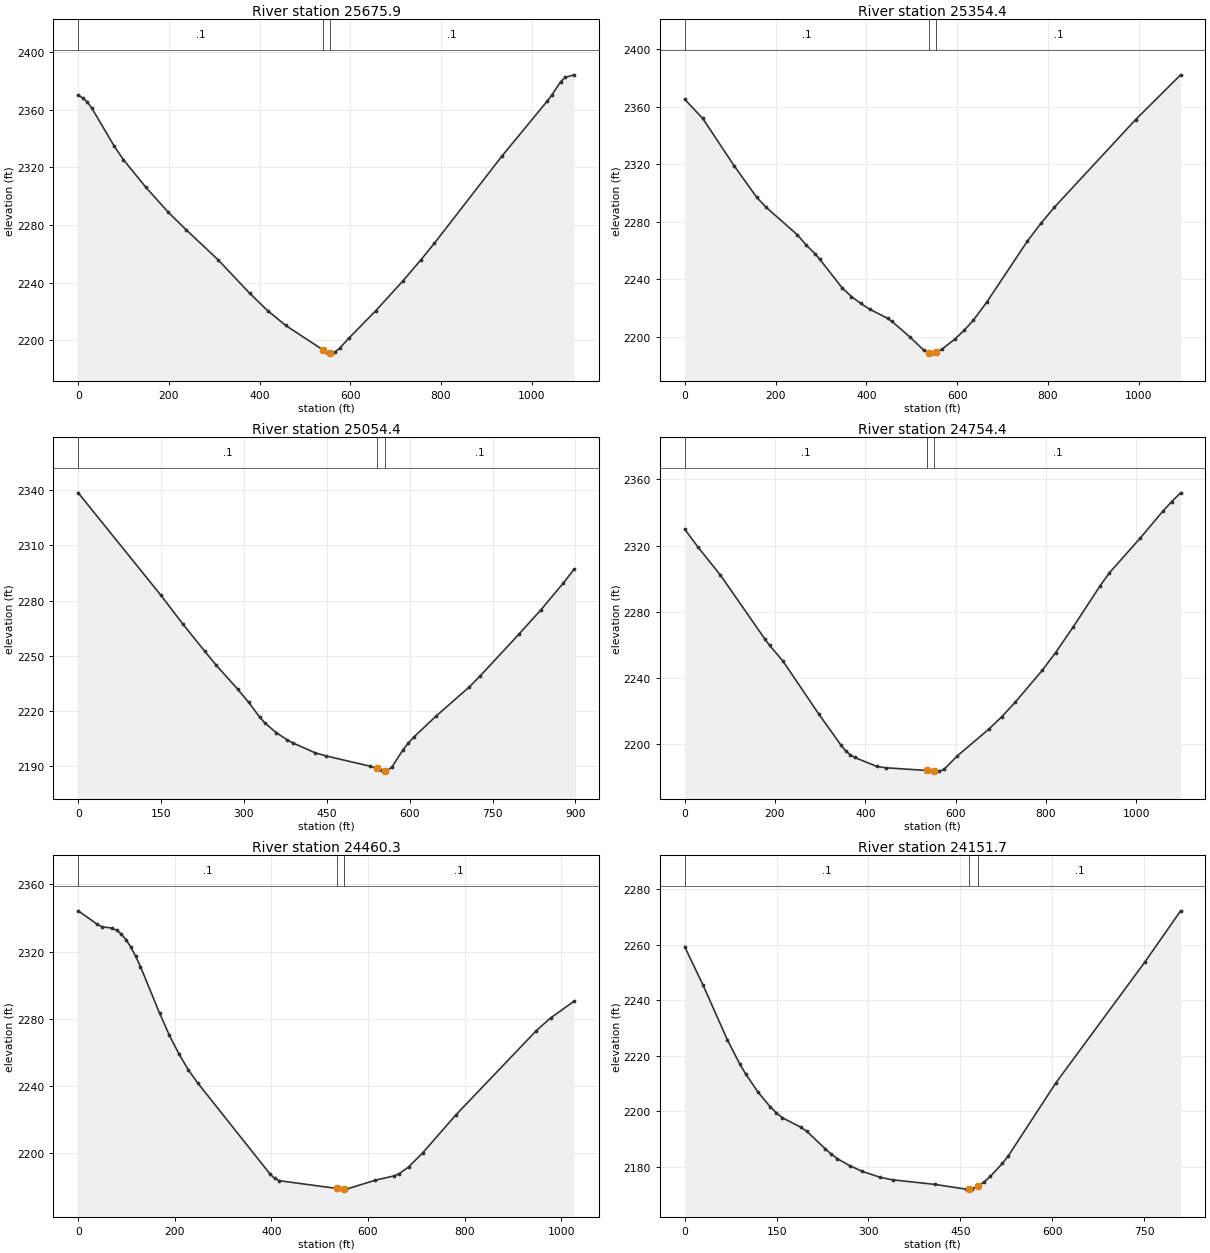
Type RM Length L Ch R = 1 ,25675.9 ,321.8,321.4,321
XS GIS Cut Line= 2
     1991921.386       376164.39     1992953.479      376525.926
#Sta/Elev= 30
       0 2370.14     9.9 2368.12    19.9 2365.35    29.8 2361.18    79.5  2334.7
    99.4 2325.43   149.1 2306.22   198.8 2288.79   238.6 2276.52   308.2 2255.98
   377.8 2232.76   417.6 2220.65   457.3  2210.4   540.5 2193.24   546.8 2191.99
   555.5 2191.25   556.7 2191.15   566.7    2192   576.6 2194.58   596.5 2201.42
   656.2 2220.59   715.8 2241.19   755.6 2255.83   785.4 2267.36   934.5 2327.86
  1033.9 2365.82  1043.9    2370  1063.8 2379.38  1073.7 2382.44  1093.6 2384.18
#Mann= 3 , 0 , 0
       0      .1       0   540.5    .045       0   555.5      .1       0
Bank Sta=540.5,555.5
XS Rating Curve= 0 ,0
Exp/Cntr=0.3,0.1

Type RM Length L Ch R = 1 ,25354.4 ,300,299.9,299.6
XS GIS Cut Line= 3
     1991830.351      376480.092     1992348.332      376652.753
     1992866.313      376825.414
#Sta/Elev= 30
       0 2365.15    39.7  2351.8   109.2 2318.79   158.8 2296.94   178.7 2290.26
   248.2 2270.93     268 2263.69   287.9  2257.5   297.8  2253.8   347.4 2233.82
   367.3 2228.07   387.2 2223.34     407 2219.31   446.7 2212.94   456.6 2210.72
   496.4 2199.82   526.2 2190.82   538.5 2188.91     546 2188.73   553.5  2189.4
   565.8 2191.28   595.6 2198.67   615.5 2204.62   635.4 2211.52   665.1 2224.11
   754.5  2266.5   784.2 2278.84     814 2290.07   992.7 2350.92    1092 2382.11
#Mann= 3 , 0 , 0
       0      .1       0   538.5    .045       0   553.5      .1       0
Bank Sta=538.5,553.5
XS Rating Curve= 0 ,0
Exp/Cntr=0.3,0.1

Type RM Length L Ch R = 1 ,25054.4 ,297.5,299.9,303.6
XS GIS Cut Line= 3
     1991749.965      376769.404     1992269.581       376941.83
     1992603.659      377046.946
#Sta/Elev= 30
       0 2338.39   149.3 2282.98   189.1 2267.37   228.9 2252.54   248.8 2245.27
   288.7 2231.91   308.6 2224.76   328.5 2216.77   338.4 2213.45   358.4 2208.38
   378.3 2204.42   388.2 2202.82     428 2197.52   447.9 2195.78   527.6  2190.2
     540 2188.94   547.5 2188.04     555 2187.62   557.5 2187.48   567.5 2189.57
   587.5 2198.82   597.5 2202.72   607.5 2205.94   647.5 2217.26   707.6 2233.04
   727.6  2239.1   797.6 2261.71   837.7 2274.99   877.7 2289.32   897.7 2297.02
#Mann= 3 , 0 , 0
       0      .1       0     540    .045       0     555      .1       0
Bank Sta=540,555
XS Rating Curve= 0 ,0
Exp/Cntr=0.3,0.1

Type RM Length L Ch R = 1 ,24754.4 ,288.9,294.2,298.3
XS GIS Cut Line= 3
     1991633.527      376977.569     1992129.795      377201.715
     1992623.428      377452.911
#Sta/Elev= 30
       0  2329.9    29.7 2319.01    79.2 2302.16   178.2 2263.34   188.1 2259.72
   217.8  2250.2     297 2218.29   346.5 2199.39   356.4 2196.13   366.3 2193.76
   376.2 2192.07   425.7 2186.65   445.5 2185.83     537  2184.2     552 2183.88
   564.3 2183.81   574.2  2184.8   603.9 2193.04   673.1 2209.03   702.8 2216.79
   732.5 2225.55   791.8 2244.62   821.5 2255.37     861 2271.08   920.4  2295.8
   940.2 2303.39  1009.4 2324.67  1058.8 2340.67  1078.6 2346.57  1098.4 2351.85
#Mann= 3 , 0 , 0
       0      .1       0     537    .045       0     552      .1       0
Bank Sta=537,552
XS Rating Curve= 0 ,0
Exp/Cntr=0.3,0.1

Type RM Length L Ch R = 1 ,24460.3 ,310.7,308.3,305.7
XS GIS Cut Line= 3
     1991547.344      377115.412     1992082.112      377526.362
     1992413.345      377646.942
#Sta/Elev= 30
       0  2344.2    39.7 2336.17    49.6 2334.72    69.4 2333.95    79.3 2332.73
    89.3  2330.4    99.2  2326.9   109.1 2322.61     119 2317.19   128.9 2311.04
   168.6  2283.3   188.4 2270.46   208.3 2259.32   228.1 2249.65     248 2241.69
   396.7 2187.96   406.6  2185.2   416.6 2183.81   535.2 2179.21   550.2 2178.81
   555.4  2178.8   614.9 2184.08   654.6 2186.71   664.5 2187.96   684.2 2191.98
   713.6 2200.45   782.1 2222.95   948.6    2273     978 2280.49  1026.9 2290.53
#Mann= 3 , 0 , 0
       0      .1       0   535.2    .045       0   550.2      .1       0
Bank Sta=535.2,550.2
XS Rating Curve= 0 ,0
Exp/Cntr=0.3,0.1

Type RM Length L Ch R = 1 ,24151.7 ,386.3,396.5,406.8
XS GIS Cut Line= 3
     1991493.738      377504.571     1991935.382      377757.353
     1992214.315      377869.217
#Sta/Elev= 30
       0 2259.26    29.9 2245.44    69.8 2225.66    89.8 2217.05    99.8 2213.34
   119.7 2206.88   139.7 2201.58   149.7 2199.41   159.6 2197.66   189.6 2194.23
   199.6 2192.73   229.5 2186.47   239.5 2184.51   249.4 2182.92   269.4  2180.4
   289.4  2178.4   319.3  2176.2   339.2 2175.32   409.1 2173.65     459 2171.97
   464.1 2172.07     469 2172.16   479.1 2173.05   488.9  2174.6   498.9 2176.57
   518.6 2181.24   528.3 2183.99   605.8 2210.22   751.2 2253.76   809.4 2272.15
#Mann= 3 , 0 , 0
       0      .1       0   464.1    .045       0   479.1      .1       0
Bank Sta=464.1,479.1
XS Rating Curve= 0 ,0
Exp/Cntr=0.3,0.1

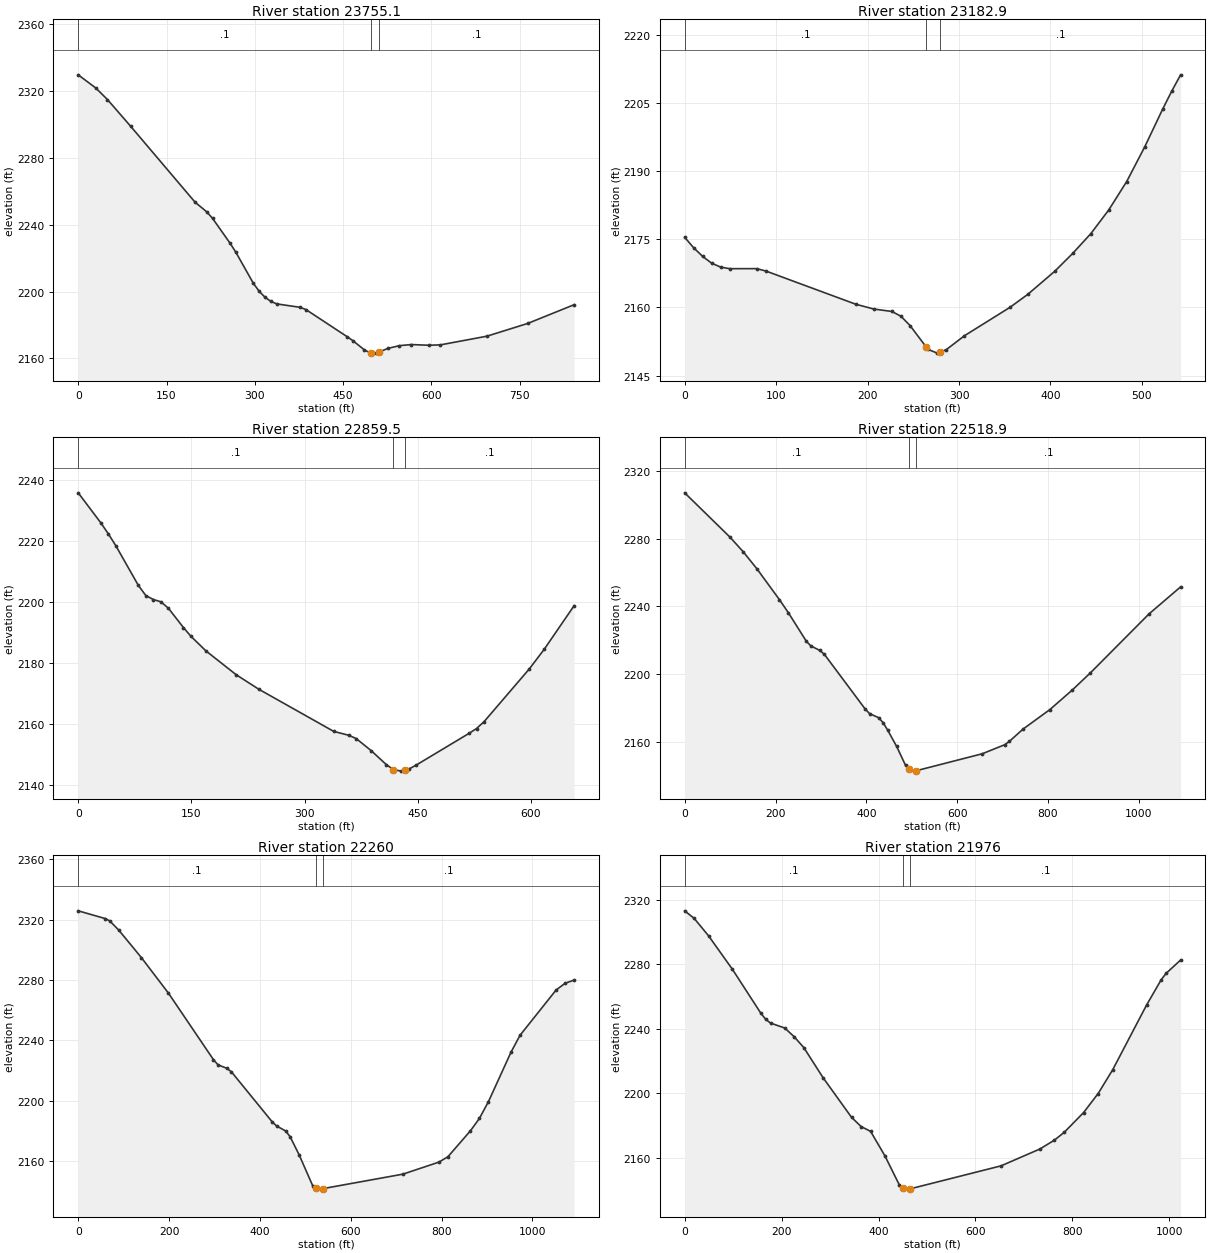
Type RM Length L Ch R = 1 ,23755.1 ,579.1,572.2,565.3
XS GIS Cut Line= 3
     1991291.287      377490.259     1991643.374      378030.475
     1991808.991       378137.98
#Sta/Elev= 30
       0 2329.75    29.8 2321.88    49.6 2314.98    89.3 2298.87   198.4 2253.54
   218.2 2247.77   228.2 2243.82   257.9 2228.98   267.8 2223.52   297.6 2204.88
   307.5 2200.14   317.4 2196.58   327.4  2194.1   337.3 2192.64     377 2190.59
   386.9 2189.22   456.3 2173.13   466.3 2170.69   486.1  2165.1   496.5 2163.23
   505.9 2163.18   511.5  2163.9   525.8    2166   545.6 2167.65   565.5 2168.31
   595.2  2167.9   615.1 2168.12   694.2 2173.32   763.3 2180.93   842.3 2192.17
#Mann= 3 , 0 , 0
       0      .1       0   496.5    .045       0   511.5      .1       0
Bank Sta=496.5,511.5
XS Rating Curve= 0 ,0
Exp/Cntr=0.3,0.1

Type RM Length L Ch R = 1 ,23182.9 ,332.2,323.4,314.5
XS GIS Cut Line= 4
     1990972.192      378076.964     1991083.359      378239.394
     1991206.089      378339.916     1991300.519      378501.174
#Sta/Elev= 30
       0 2175.42     9.8 2173.12    19.7 2171.21    29.5 2169.73    39.4 2168.86
    49.2 2168.52    78.7 2168.53    88.6 2168.02     187 2160.71   206.7 2159.65
   226.6 2159.11   236.5 2158.06   246.4 2156.02   264.4 2151.22   266.2 2150.77
   276.2 2149.95   279.4  2150.2   286.1 2150.72   305.9 2153.77   355.5 2159.99
   375.1 2162.86   404.6 2167.94   424.3 2171.88     444  2176.2   463.7 2181.43
   483.3 2187.67     503 2195.29   522.7 2203.62   532.5 2207.53   542.3 2211.15
#Mann= 3 , 0 , 0
       0      .1       0   264.4    .045       0   279.4      .1       0
Bank Sta=264.4,279.4
XS Rating Curve= 0 ,0
Exp/Cntr=0.3,0.1

Type RM Length L Ch R = 1 ,22859.5 ,341.5,340.6,339.8
XS GIS Cut Line= 2
     1990574.132      378444.516     1991203.183      378634.829
#Sta/Elev= 30
       0 2235.82    29.9 2225.99    39.8  2222.4    49.8 2218.48    79.7 2205.43
    89.6  2202.1    99.6 2200.79   109.5 2200.06   119.5 2197.94   139.4  2191.6
   149.4 2188.72   169.3 2183.92   209.1 2176.15     239 2171.39   338.6  2157.5
   358.5 2156.23   368.4 2155.15   388.4 2151.15   408.3  2146.6   417.8 2144.96
   428.2 2144.46   432.8 2144.77   438.1 2145.12   448.1 2146.48   517.8 2156.84
   527.8 2158.44   537.7 2160.66   597.5 2177.93   617.4 2184.41   657.2 2198.79
#Mann= 3 , 0 , 0
       0      .1       0   417.8    .045       0   432.8      .1       0
Bank Sta=417.8,432.8
XS Rating Curve= 0 ,0
Exp/Cntr=0.3,0.1

Type RM Length L Ch R = 1 ,22518.9 ,259.1,258.9,258.8
XS GIS Cut Line= 3
      1990396.29      378765.483     1990924.504      378903.708
     1991452.718      379041.932
#Sta/Elev= 30
       0 2307.06    99.3 2281.02     129 2272.22   158.8 2262.29   208.5 2244.03
   228.3 2236.27     268 2219.36     278 2216.62   297.8 2213.97   307.8 2211.62
   397.1 2179.51     407 2176.69   426.9  2174.3   436.8 2171.35   446.7 2167.06
   466.6 2157.37   486.4  2146.1   494.5 2143.72   496.4 2143.16   506.3 2142.72
   509.5 2142.93   655.2 2152.97   704.8 2158.33   714.8 2160.25   744.6 2167.46
   804.1 2179.06   853.8  2190.7   893.4 2200.76  1022.5 2235.58    1092 2251.53
#Mann= 3 , 0 , 0
       0      .1       0   494.5    .045       0   509.5      .1       0
Bank Sta=494.5,509.5
XS Rating Curve= 0 ,0
Exp/Cntr=0.3,0.1

Type RM Length L Ch R = 1 ,22260   ,285.8,284,282.2
XS GIS Cut Line= 3
     1990300.635      379012.247     1990829.891      379146.425
     1991359.148      379280.602
#Sta/Elev= 30
       0 2325.87    59.6 2320.73    69.5 2319.16    89.4 2313.04     139 2294.89
   198.6 2271.33   297.8 2227.18   307.8 2223.76   327.6  2221.4   337.5 2219.07
   426.9 2186.04   436.8 2183.21   456.6 2179.94   466.6 2176.11   486.4  2164.1
   516.2 2143.67   523.3 2142.02   526.2 2141.34   538.3 2141.65   714.8 2151.26
   794.2 2159.24     814  2162.8   863.7 2180.04   883.5 2188.29   903.4 2199.42
     953 2232.17   972.9 2243.38  1052.3 2273.38  1072.2 2277.84    1092 2279.98
#Mann= 3 , 0 , 0
       0      .1       0   523.3    .045       0   538.3      .1       0
Bank Sta=523.3,538.3
XS Rating Curve= 0 ,0
Exp/Cntr=0.3,0.1

Type RM Length L Ch R = 1 ,21976   ,299.6,302.5,305.5
XS GIS Cut Line= 3
     1990305.369      379321.992     1990728.126       379414.97
     1991310.285      379513.859
#Sta/Elev= 30
       0 2313.03    19.7 2308.31    49.2 2297.56    98.4 2276.81   157.4 2249.42
   167.2 2245.76   177.1 2243.43   206.6 2240.32   226.3 2234.83   245.9 2228.18
   285.3 2209.65   344.3 2184.96     364 2179.25   383.7 2176.23   413.2 2161.07
   442.9 2143.06   450.6 2141.04   462.9 2140.42   465.6 2140.63     653 2154.87
   733.1 2165.32   763.1 2170.84   783.2 2175.65   823.2 2187.92   853.2  2199.7
   883.2 2214.44   953.3 2254.68   983.3 2270.26   993.3  2274.2  1023.4 2282.53
#Mann= 3 , 0 , 0
       0      .1       0   450.6    .045       0   465.6      .1       0
Bank Sta=450.6,465.6
XS Rating Curve= 0 ,0
Exp/Cntr=0.3,0.1

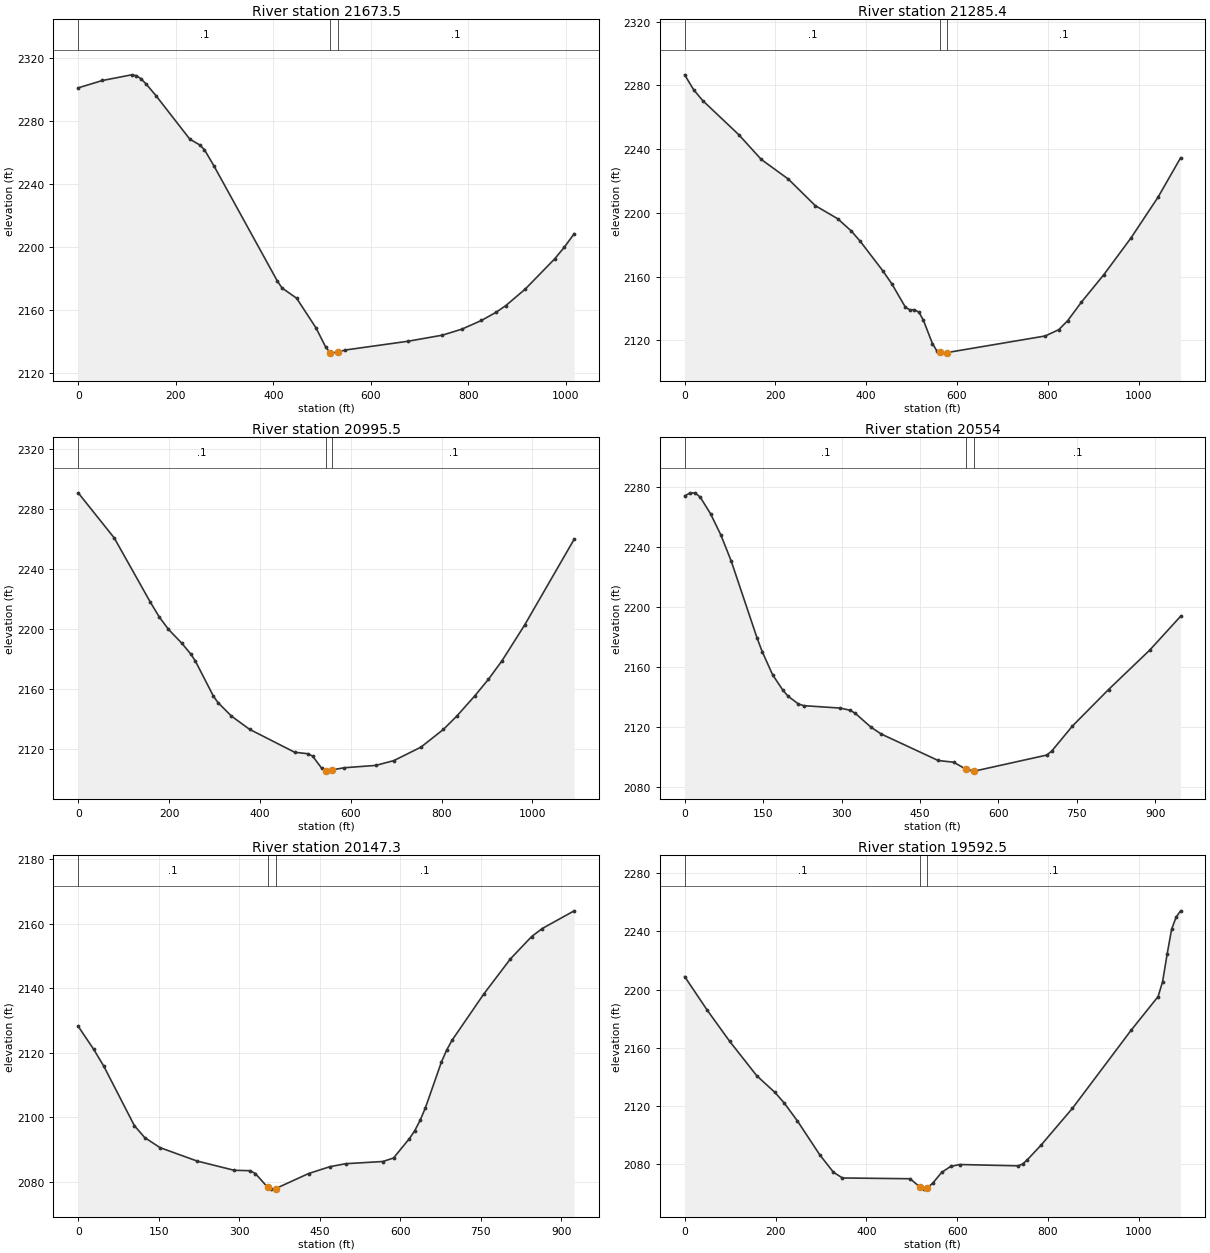
Type RM Length L Ch R = 1 ,21673.5 ,382.6,388,393.4
XS GIS Cut Line= 3
     1990176.552      379554.013     1990822.556      379754.919
     1991162.506      379740.391
#Sta/Elev= 30
       0 2300.84    49.7 2305.51   109.4  2309.1   119.4 2308.55   129.3 2306.46
   139.3 2303.26   159.2 2295.99   228.8 2268.32   248.7 2264.74   258.7 2261.68
   278.6 2251.19   407.9 2178.55   417.8 2173.97   447.7 2167.48   487.5 2148.66
   507.4  2136.5     517 2132.76   517.3 2132.64     532 2133.29   547.2  2134.6
   676.5 2140.19   746.6 2144.03   786.6 2147.85   826.6 2153.34   856.7 2158.53
   876.7 2162.79   916.7  2173.3   976.8 2192.39   996.8 2199.87  1016.8 2208.36
#Mann= 3 , 0 , 0
       0      .1       0     517    .045       0     532      .1       0
Bank Sta=517,532
XS Rating Curve= 0 ,0
Exp/Cntr=0.3,0.1

Type RM Length L Ch R = 1 ,21285.4 ,291.8,290,288.2
XS GIS Cut Line= 3
     1989993.414      379783.771     1990475.337      380040.114
     1990944.893       380320.31
#Sta/Elev= 30
       0 2286.61    19.8 2277.24    39.7 2270.46   119.1 2249.09   168.7 2233.54
   228.3 2221.21   287.8 2204.54   337.4 2196.28   367.2  2188.6   387.1 2182.07
   436.7 2163.61   456.5 2155.42   486.3 2140.84   496.2 2139.13   506.2 2139.24
   516.1  2137.7     526 2132.64   545.9 2117.99   555.8 2113.32   562.7 2112.41
   565.7 2112.01   577.7 2112.34   794.4 2122.77   824.2 2126.72   844.1 2132.44
   873.9 2143.92   923.6 2161.27   983.3 2184.25    1043 2209.87  1092.7 2234.58
#Mann= 3 , 0 , 0
       0      .1       0   562.7    .045       0   577.7      .1       0
Bank Sta=562.7,577.7
XS Rating Curve= 0 ,0
Exp/Cntr=0.3,0.1

Type RM Length L Ch R = 1 ,20995.5 ,443,441.5,440.1
XS GIS Cut Line= 3
     1989861.829      380061.351     1990351.306      380303.276
     1990840.783      380545.202
#Sta/Elev= 30
       0 2290.72    79.4 2260.68   158.8 2217.99   178.7 2208.03   198.6 2199.98
   228.3 2190.61   248.2 2183.33   258.1 2178.76   297.8  2155.4   307.8 2151.19
   337.5 2142.17   377.2 2133.43   476.5 2118.16   506.3 2117.14   516.2 2115.57
   536.1 2107.52   544.7 2105.84     546 2105.59   559.7 2106.45   585.7 2107.84
   655.2  2109.4   694.9 2112.58   754.5 2121.52   804.1 2133.33   833.9  2142.3
   873.6  2155.8   903.4 2166.74   933.2 2179.04   982.8 2202.69    1092 2259.85
#Mann= 3 , 0 , 0
       0      .1       0   544.7    .045       0   559.7      .1       0
Bank Sta=544.7,559.7
XS Rating Curve= 0 ,0
Exp/Cntr=0.3,0.1

Type RM Length L Ch R = 1 ,20554   ,407.1,406.5,406
XS GIS Cut Line= 3
     1989657.709      380492.167     1990287.935      380754.428
     1990547.982      380809.634
#Sta/Elev= 30
       0 2273.77     9.9 2275.63    19.8 2275.81    29.7 2272.95    49.5 2261.83
    69.2 2247.73      89 2230.35   138.5 2179.01   148.4 2169.86   168.2 2154.55
     188 2144.18   197.9 2140.23   217.6 2135.09   227.5 2133.98   296.8 2132.37
   316.6 2130.92   326.5 2128.78   356.2 2119.66   375.9 2115.07   484.8 2097.43
   514.4 2096.27   538.5 2091.53   553.5 2090.35     554 2090.34   692.5 2101.05
   702.3 2103.83   741.7 2120.45   810.6  2144.7   889.4 2170.99   948.5 2193.56
#Mann= 3 , 0 , 0
       0      .1       0   538.5    .045       0   553.5      .1       0
Bank Sta=538.5,553.5
XS Rating Curve= 0 ,0
Exp/Cntr=0.3,0.1

Type RM Length L Ch R = 1 ,20147.3 ,552.3,554.9,557.4
XS GIS Cut Line= 3
     1989711.184       380870.65      1989808.52      380999.947
     1990518.988      381276.203
#Sta/Elev= 30
       0 2128.25    28.6 2121.19    47.6 2115.92   104.7 2097.46   123.8 2093.79
   152.3 2090.67   221.2 2086.52   290.5 2083.64   320.2 2083.51   330.1 2082.62
   353.1 2078.36   359.8  2077.8   368.1 2077.98   429.1 2082.62   468.7 2084.74
   498.4 2085.68   567.7 2086.36   587.5 2087.44   617.2 2093.48   627.1 2095.92
     637 2099.09   646.9 2102.98   676.6  2117.1   686.5 2120.88   696.4 2123.89
   755.8 2138.28   805.3 2149.14   844.9 2156.07   864.7 2158.56   924.1 2164.04
#Mann= 3 , 0 , 0
       0      .1       0   353.1    .045       0   368.1      .1       0
Bank Sta=353.1,368.1
XS Rating Curve= 0 ,0
Exp/Cntr=0.3,0.1

Type RM Length L Ch R = 1 ,19592.5 ,240.2,238,235.8
XS GIS Cut Line= 3
     1989282.795      381323.558     1989765.663      381578.404
     1990251.224      381828.177
#Sta/Elev= 30
       0 2208.98    49.6 2185.92    99.3 2164.42   158.8 2140.82   198.5 2129.47
   218.4 2122.42   248.2 2109.82   297.8 2086.35   327.6 2074.52   347.4 2070.59
   496.4 2070.06   518.3 2064.31   526.1 2062.92   533.3 2063.61     546 2066.94
   565.8 2074.41   585.7 2078.54   605.6 2079.83   734.6 2078.93   744.6 2080.32
   754.5 2083.12   784.3 2093.02   853.8 2118.48   982.8 2172.03  1042.4 2195.25
  1052.3 2205.48  1062.2 2224.24  1072.2 2241.54  1082.1 2249.86    1092 2254.18
#Mann= 3 , 0 , 0
       0      .1       0   518.3    .045       0   533.3      .1       0
Bank Sta=518.3,533.3
XS Rating Curve= 0 ,0
Exp/Cntr=0.3,0.1