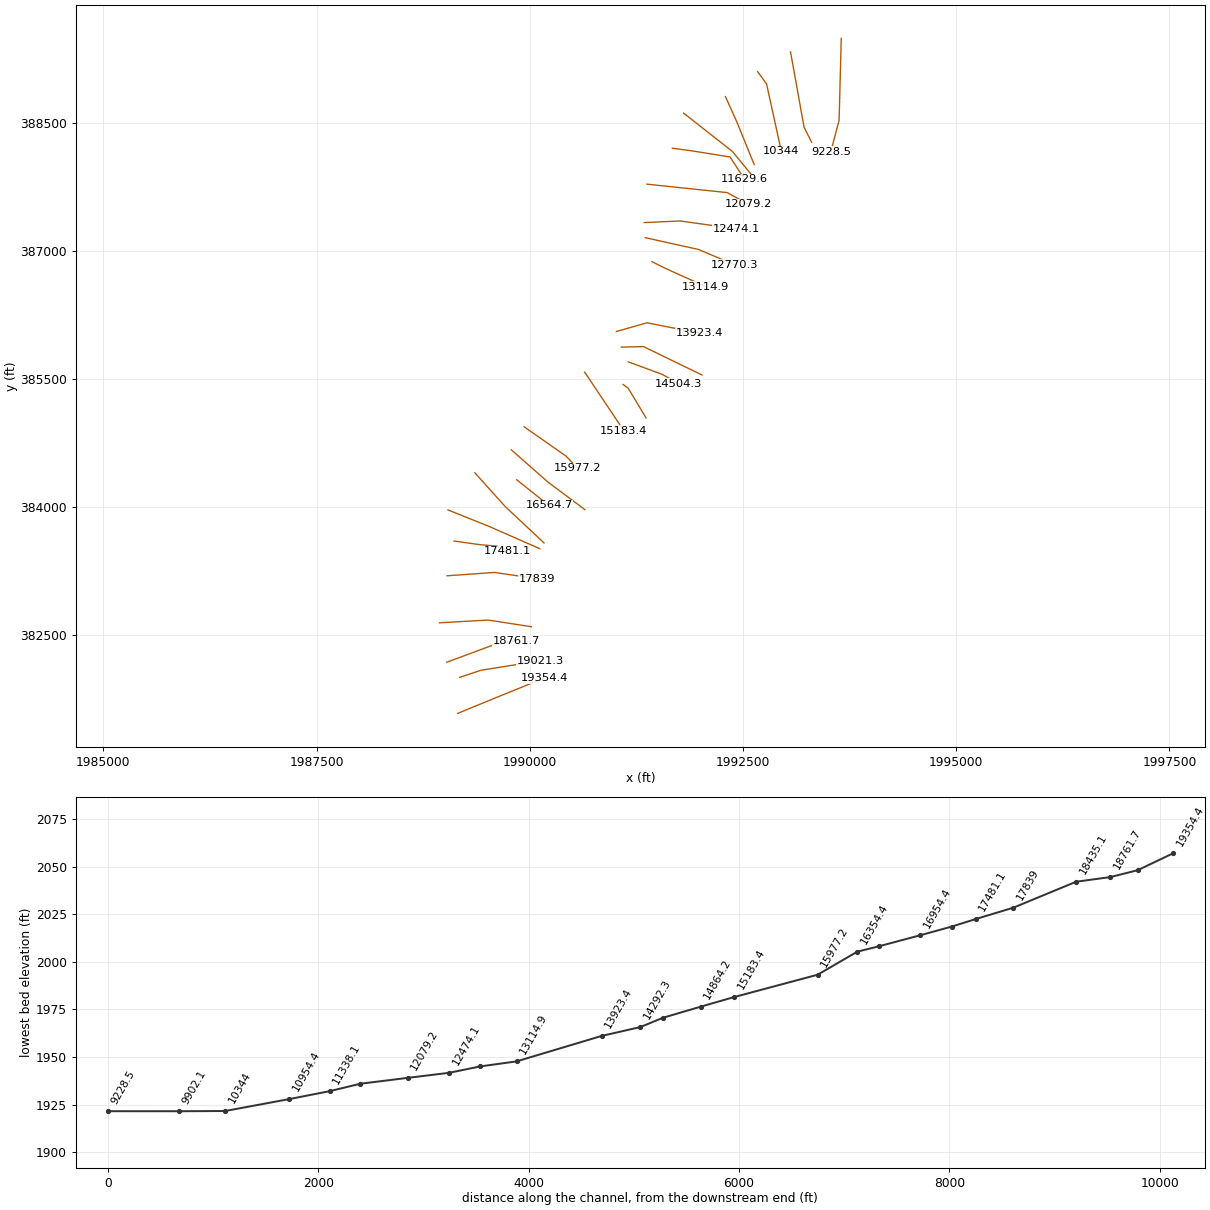
HEC-RAS study BrakensCrk.prj: BrakensCrk

--- BrakensCrk.g01 (geometry) --- (continued)

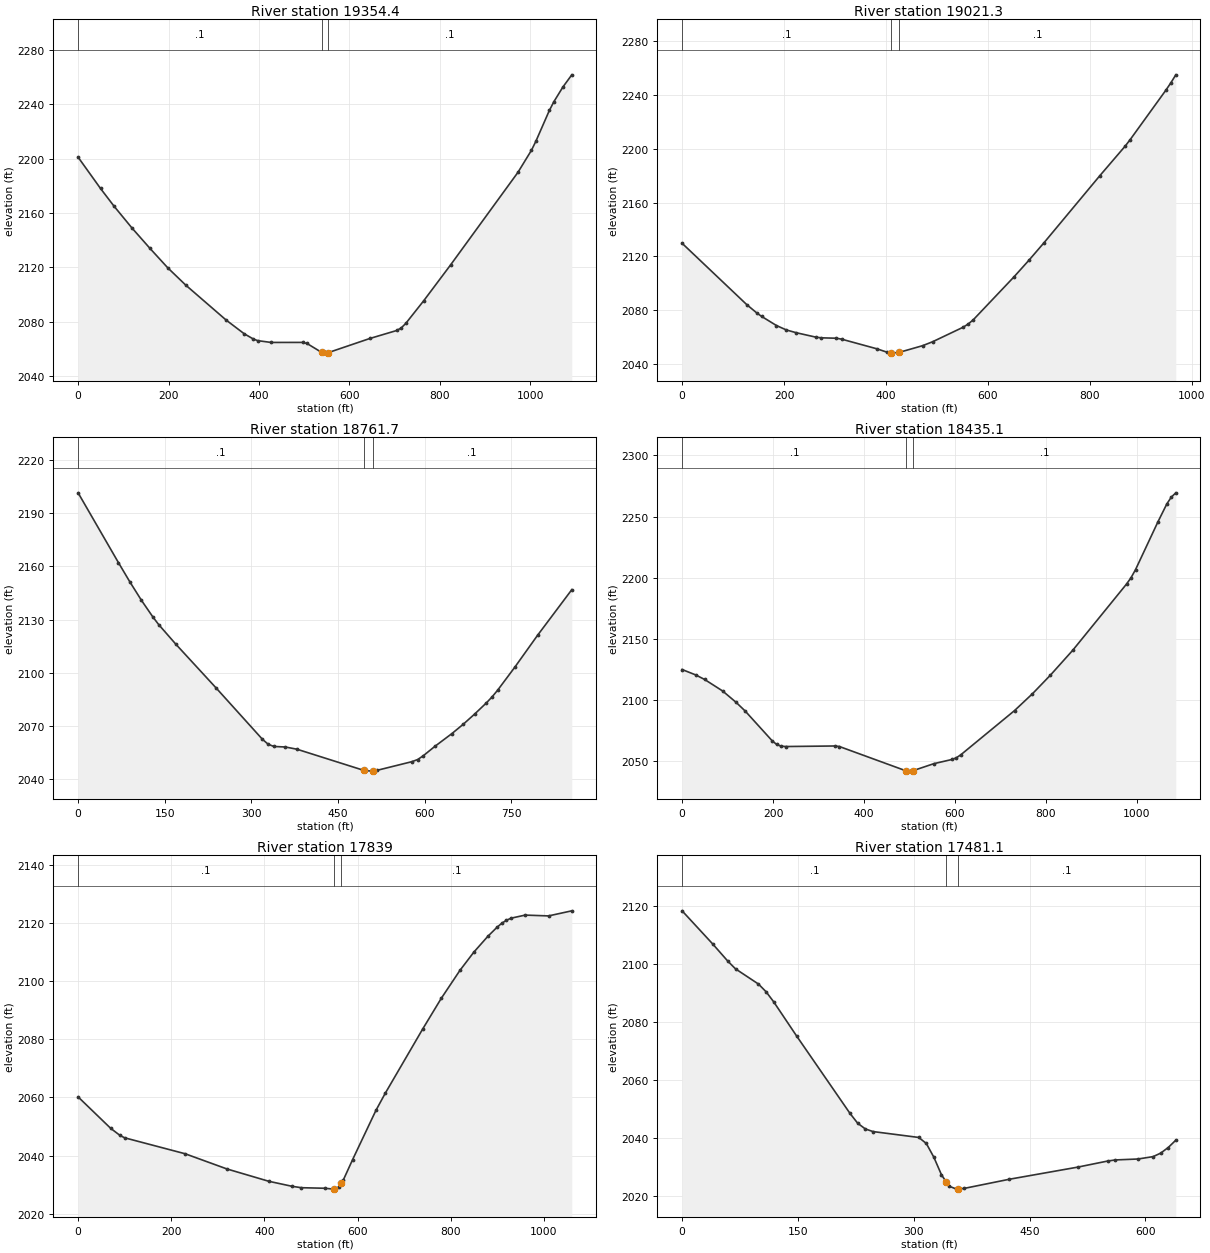
Type RM Length L Ch R = 1 ,19354.4 ,338.3,333.1,328
XS GIS Cut Line= 3
     1989155.852      381583.332     1989660.993       381790.57
     1990167.104       381995.45
#Sta/Elev= 30
       0 2201.01    49.6 2177.99    79.4 2165.02   119.1 2148.96   158.8 2134.01
   198.5 2119.59   238.2 2106.91   327.6 2081.19   367.3 2071.19   387.2 2067.38
   397.1 2066.11   426.9 2064.78   496.4  2064.8   506.3 2064.01   538.5  2057.5
     546 2056.92   553.5 2057.32   645.3 2067.69   704.8 2073.57   714.8 2075.48
   724.7 2078.75   764.4 2095.41     824 2121.84   972.9 2189.88  1002.7 2206.06
  1012.6 2212.77  1042.4 2235.41  1052.3 2241.78  1072.2 2252.57    1092 2261.58
#Mann= 3 , 0 , 0
       0      .1       0   538.5    .045       0   553.5      .1       0
Bank Sta=538.5,553.5
XS Rating Curve= 0 ,0
Exp/Cntr=0.3,0.1

Type RM Length L Ch R = 1 ,19021.3 ,255.3,259.7,264
XS GIS Cut Line= 3
     1989178.015      382005.267     1989427.892      382088.076
     1990124.639      382200.093
#Sta/Elev= 30
       0  2129.8   126.8 2084.21   146.2 2078.11     156 2075.43   185.2 2068.63
   204.7 2065.33   224.2 2063.27   263.2 2059.94   273.2 2059.49     303 2059.19
   312.9 2058.51   382.5  2051.3   402.4 2048.78   410.2 2048.25   412.3 2048.11
   425.2 2048.58     472 2053.65   491.8  2056.6   551.5 2067.37   561.4 2069.74
   571.4 2072.88   650.9 2104.65   680.7  2117.2   710.5 2130.32   819.8 2180.06
   869.5 2202.04   879.5 2206.97   949.1 2243.49     959 2249.01   968.9 2255.08
#Mann= 3 , 0 , 0
       0      .1       0   410.2    .045       0   425.2      .1       0
Bank Sta=410.2,425.2
XS Rating Curve= 0 ,0
Exp/Cntr=0.3,0.1

Type RM Length L Ch R = 1 ,18761.7 ,333.2,326.5,319.8
XS GIS Cut Line= 3
     1989026.927      382182.506     1989568.812      382382.989
     1989840.481      382435.289
#Sta/Elev= 30
       0 2201.56    69.7 2162.23    89.7 2151.24   109.6 2140.91   129.5 2131.46
   139.5 2127.19   169.4 2116.04   239.1 2091.34   318.8 2062.54   328.7 2059.72
   338.7 2058.42   358.6 2058.12   378.6 2056.88   494.8 2044.89     508  2044.5
   509.8 2044.59     518    2045   577.8 2049.85   587.7 2051.05   597.5 2053.21
   617.3 2058.44     647 2065.71   666.7    2071   686.5 2076.78   706.2 2082.89
   716.1 2086.27     726 2090.15   755.6 2103.08   795.2 2121.18   854.4 2146.91
#Mann= 3 , 0 , 0
       0      .1       0   494.8    .045       0   509.8      .1       0
Bank Sta=494.8,509.8
XS Rating Curve= 0 ,0
Exp/Cntr=0.3,0.1

Type RM Length L Ch R = 1 ,18435.1 ,595.8,596,591.8
XS GIS Cut Line= 3
     1988941.213      382644.488     1989513.606      382676.449
     1990019.591      382598.237
#Sta/Elev= 30
       0 2125.03    29.6 2120.66    49.4 2116.93      89 2107.52   118.6 2098.26
   138.4 2091.23   197.7 2066.94   207.6 2063.89   217.4 2062.43   227.3 2062.13
   336.1 2062.58     346 2062.11   493.1 2042.16   504.1 2042.04   508.1 2042.48
   553.5 2048.14     593 2051.54   602.8 2052.92   612.7 2055.39   730.8  2091.5
   770.2 2105.24   809.6 2120.41   858.8 2140.78     977 2194.85   986.8 2199.98
   996.7 2206.57  1045.9 2245.56  1065.6  2260.3  1075.4 2265.83  1085.3 2269.35
#Mann= 3 , 0 , 0
       0      .1       0   493.1    .045       0   508.1      .1       0
Bank Sta=493.1,508.1
XS Rating Curve= 0 ,0
Exp/Cntr=0.3,0.1

Type RM Length L Ch R = 1 ,17839   ,361.3,357.8,358.9
XS GIS Cut Line= 3
     1989029.832       383195.09     1989587.698      383234.315
     1990083.094      383161.676
#Sta/Elev= 30
       0 2060.18    69.9 2049.37    89.9 2046.92    99.9  2046.1   229.7 2040.61
   319.6 2035.37   409.4 2031.13   459.4  2029.4   479.4 2028.92   529.3 2028.73
   549.3 2028.43   549.6 2028.45   559.2 2029.14   564.6 2030.43   569.3 2031.55
   589.3 2038.58   639.4 2055.54   659.4 2061.43   739.5 2083.47   779.6 2094.09
   819.6  2103.7   849.6 2110.01   879.7 2115.46   899.7 2118.62   909.7 2119.96
   919.7 2120.99   929.8 2121.71   959.8 2122.76  1009.9 2122.48  1059.9 2124.23
#Mann= 3 , 0 , 0
       0      .1       0   549.6    .045       0   564.6      .1       0
Bank Sta=549.6,564.6
XS Rating Curve= 0 ,0
Exp/Cntr=0.3,0.1

Type RM Length L Ch R = 1 ,17481.1 ,233.3,226.6,219.2
XS GIS Cut Line= 4
      1989112.64      383601.867      1989416.27      383559.737
     1989621.098      383542.149     1989734.428      383484.192
#Sta/Elev= 30
       0 2118.26    39.6 2106.86    59.3 2100.91    69.2 2098.28    98.9 2093.05
   108.8 2090.39   118.7  2086.9   148.3 2075.17   217.5  2048.5   227.4 2045.14
   237.3 2043.17   247.2 2042.27   306.5 2040.24   316.3 2038.17   326.1  2033.4
   335.9  2027.4   342.3 2024.83   345.7 2023.47   355.5 2022.45   357.3  2022.5
   365.3  2022.7     424 2025.86   512.1 2030.01   551.3 2032.13   561.1  2032.5
   590.4 2032.82     610 2033.64   619.8 2034.84   629.6 2036.78   639.4  2039.3
#Mann= 3 , 0 , 0
       0      .1       0   342.3    .045       0   357.3      .1       0
Bank Sta=342.3,357.3
XS Rating Curve= 0 ,0
Exp/Cntr=0.3,0.1

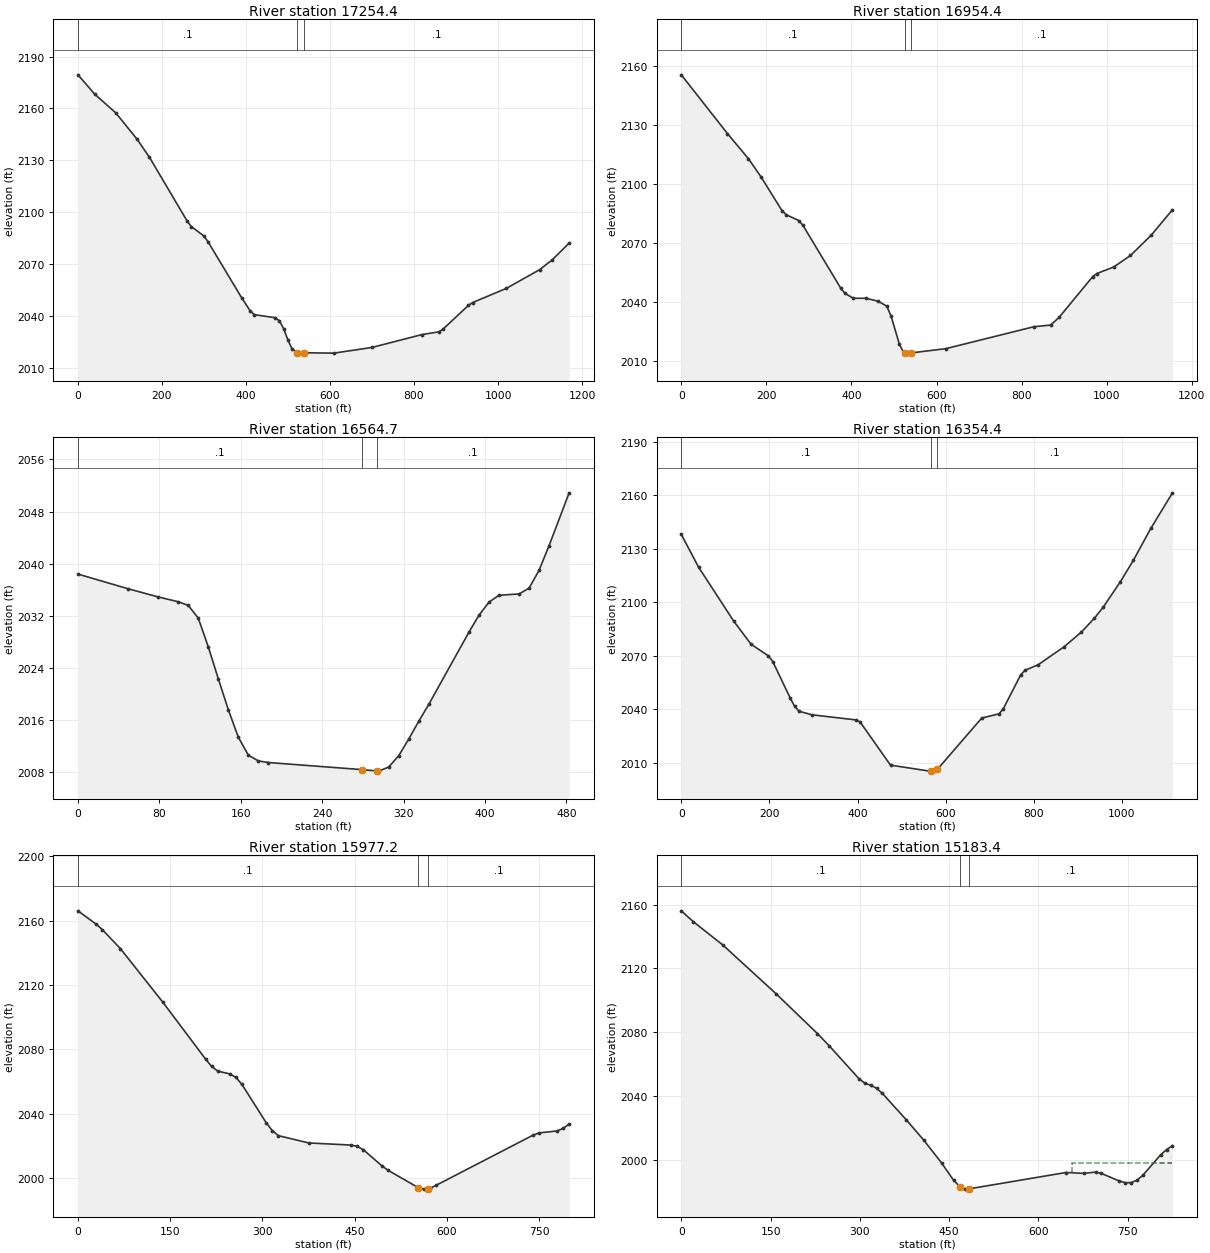
Type RM Length L Ch R = 1 ,17254.4 ,310.2,300,292.4
XS GIS Cut Line= 3
     1989041.343      383966.705     1989532.796      383769.833
     1990118.373      383512.049
#Sta/Elev= 30
       0 2179.46      40 2168.25    89.9 2157.48   139.8 2142.51   169.8 2131.92
   259.7 2094.97   269.7 2091.72   299.7 2086.28   309.7  2082.9   389.6 2050.54
   409.6 2043.08   419.5 2040.78   469.5 2038.98   479.5 2037.21   489.5  2032.7
   499.4 2026.33   509.4 2021.07   521.9 2018.77   536.9 2018.72   609.4 2018.52
   699.4 2021.79   819.3 2029.27   859.3 2030.84   869.3 2032.47   929.3 2046.11
   939.3 2047.76  1019.3 2055.92  1099.2 2066.82  1129.2 2072.52  1169.2  2082.2
#Mann= 3 , 0 , 0
       0      .1       0   521.9    .045       0   536.9      .1       0
Bank Sta=521.9,536.9
XS Rating Curve= 0 ,0
Exp/Cntr=0.3,0.1

Type RM Length L Ch R = 1 ,16954.4 ,384.4,389.6,392.1
XS GIS Cut Line= 3
     1989356.618      384401.472     1989712.866      384005.639
     1990167.065       383580.26
#Sta/Elev= 30
       0 2155.54   108.5 2125.66   157.8 2112.88   187.4 2103.63   236.7 2086.45
   246.5 2084.39   276.1 2081.41     286 2078.95   374.8 2047.02   384.6  2044.4
   404.3 2041.86   433.9 2041.85   463.5 2040.33   483.2 2037.77   493.1 2032.88
   512.8 2018.41   522.7 2014.23     525 2014.16   532.5 2013.95     540 2014.06
   621.4  2016.2   828.9 2027.38   868.4 2028.23   888.1 2032.12   967.2 2052.88
     977 2054.44  1016.5 2057.76    1056 2063.62  1105.4 2074.08  1154.8 2086.94
#Mann= 3 , 0 , 0
       0      .1       0     525    .045       0     540      .1       0
Bank Sta=525,540
XS Rating Curve= 0 ,0
Exp/Cntr=0.3,0.1

Type RM Length L Ch R = 1 ,16564.7 ,213,210.3,210.4
XS GIS Cut Line= 2
     1989847.744      384319.538     1990225.466      384018.814
#Sta/Elev= 30
       0 2038.42    49.3 2036.17    78.8 2034.92    98.5 2034.18   108.4 2033.62
   118.2 2031.68   128.1 2027.26     138 2022.34   147.8 2017.62   157.6 2013.41
   167.5 2010.65   177.4 2009.77   187.2 2009.53   279.2 2008.44   294.2 2008.23
   295.6 2008.21   305.4 2008.84   315.3 2010.58   325.2 2013.15     335 2015.86
   344.9 2018.47   384.3 2029.52   394.1  2032.1     404 2034.12   413.8 2035.17
   433.6 2035.38   443.4 2036.26   453.2    2039   463.1  2042.8   482.8 2050.88
#Mann= 3 , 0 , 0
       0      .1       0   279.2    .045       0   294.2      .1       0
Bank Sta=279.2,294.2
XS Rating Curve= 0 ,0
Exp/Cntr=0.3,0.1

Type RM Length L Ch R = 1 ,16354.4 ,374.7,377.2,377.9
XS GIS Cut Line= 3
     1989782.903      384671.704     1990213.586      384292.691
     1990647.493      383969.387
#Sta/Elev= 30
       0 2138.09    39.6  2119.6   118.7 2089.57   158.3  2076.5   197.8 2069.96
   207.7 2066.74   247.3 2046.24   257.2 2041.69   267.1 2038.91   296.7  2036.9
   395.7 2034.06   405.6 2032.97   474.8 2008.67   563.8  2005.3   566.2 2005.32
   581.2  2006.3   681.9  2035.1   721.3 2037.46   731.1 2040.42   770.5 2059.42
   780.3  2061.9   809.8 2064.96   868.9 2075.09   908.2 2083.36   937.7 2091.14
   957.4 2097.21   996.8  2111.7  1026.3 2123.72  1065.6 2141.51  1114.8 2161.46
#Mann= 3 , 0 , 0
       0      .1       0   566.2    .045       0   581.2      .1       0
Bank Sta=566.2,581.2
XS Rating Curve= 0 ,0
Exp/Cntr=0.3,0.1

Type RM Length L Ch R = 1 ,15977.2 ,802.1,793.8,785.5
XS GIS Cut Line= 3
     1989933.953      384941.018     1990427.402      384595.565
      1990562.51      384453.193
#Sta/Elev= 30
       0 2166.09    29.6 2157.78    39.5 2154.45    69.1 2142.56   138.2 2109.23
   207.4 2074.02   217.2 2069.49   227.1 2066.56   246.9 2064.75   256.7 2062.67
   266.6 2058.24   306.1 2034.43     316  2029.5   325.9 2026.42   375.2 2021.89
   444.4 2020.56   454.2 2019.72   464.1 2017.64   493.7 2007.81   503.6 2005.06
   553.3 1994.09   562.8  1993.2   568.3  1993.5   572.7 1993.74   582.6 1995.64
   739.8 2026.71   749.6 2028.11     779 2029.35   788.8  2030.9   798.6 2033.64
#Mann= 3 , 0 , 0
       0      .1       0   553.3    .045       0   568.3      .1       0
Bank Sta=553.3,568.3
XS Rating Curve= 0 ,0
Exp/Cntr=0.3,0.1

Type RM Length L Ch R = 1 ,15183.4 ,320.2,319.2,318.1
XS GIS Cut Line= 2
     1990643.865      385580.547     1991102.942      384894.837
#Sta/Elev= 30
       0 2156.06    19.9 2149.33    69.6 2134.68   159.1 2104.08   228.7 2079.06
   248.6 2071.35   298.3 2050.81   308.2 2047.96   318.2 2046.67   328.1 2044.71
     338 2041.46   377.8 2025.02   407.6 2012.07   437.4 1997.82   457.3 1987.12
   468.8 1982.73   477.2 1981.46   483.8 1981.66   646.2 1991.89   676.1 1991.36
     696 1992.13   705.9 1991.28   735.7 1986.59   745.7  1985.5   755.6 1985.52
   765.5 1987.06   775.5 1990.21   805.3 2002.98   815.2 2006.28   825.2 2008.75
#Mann= 3 , 0 , 0
       0      .1       0   468.8    .045       0   483.8      .1       0
#XS Ineff= 2 , 0
                          656.32         1997.67
Permanent Ineff=
       F       F
Bank Sta=468.8,483.8
XS Rating Curve= 0 ,0
Exp/Cntr=0.3,0.1

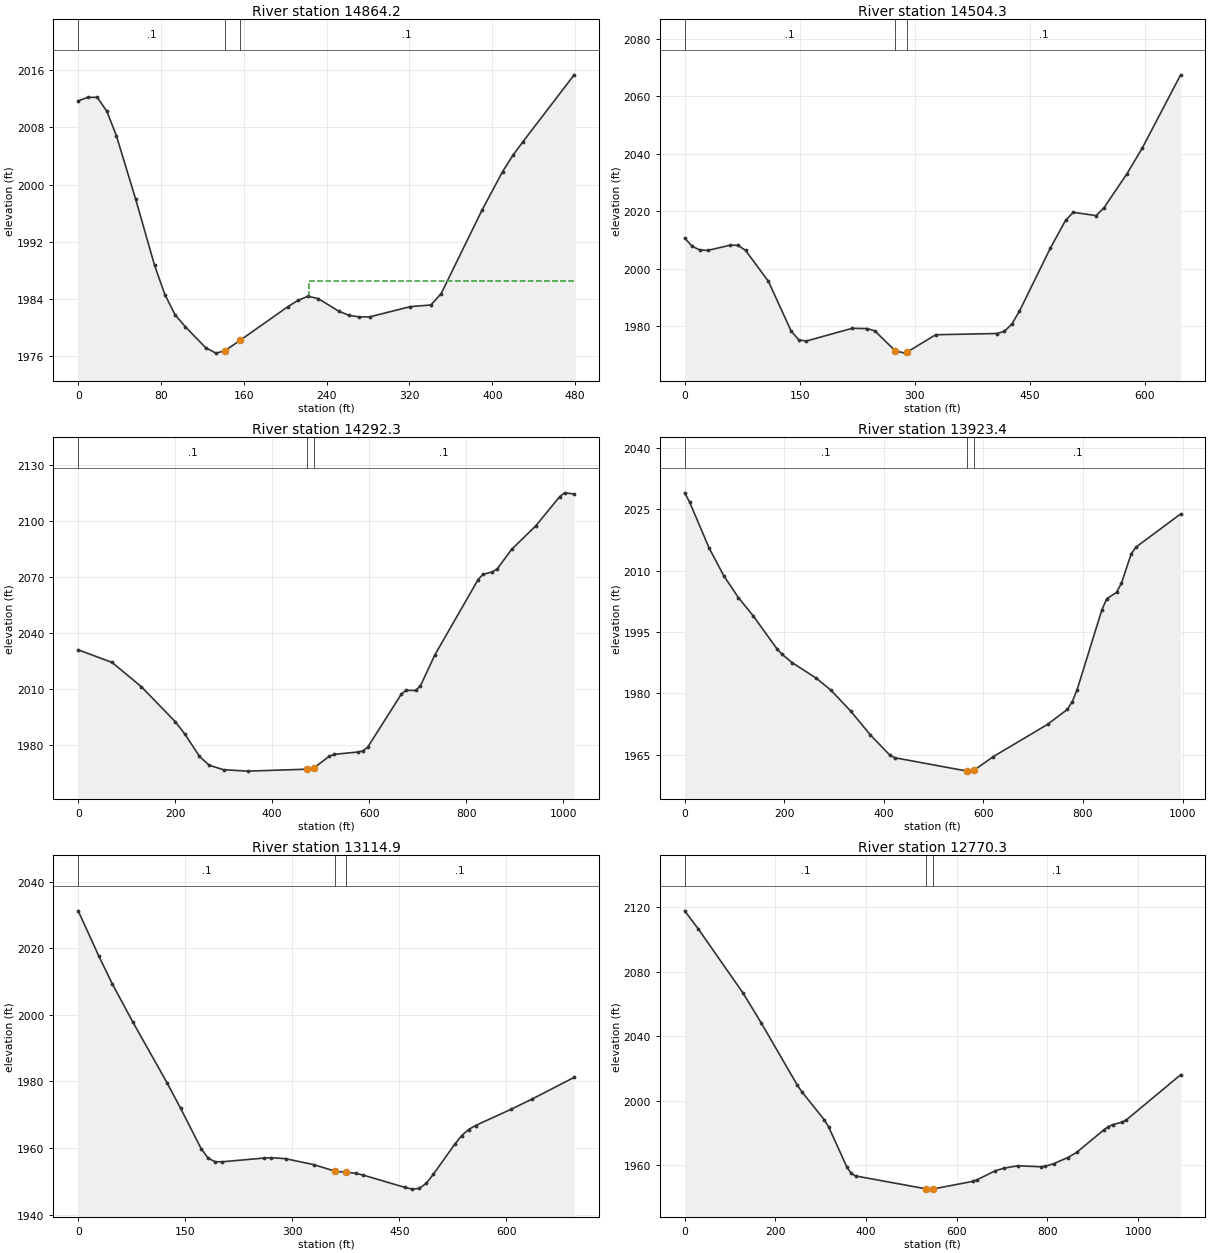
Type RM Length L Ch R = 1 ,14864.2 ,344.2,359.5,374.8
XS GIS Cut Line= 3
     1991094.225      385436.722      1991153.65       385392.95
     1991362.989      385045.925
#Sta/Elev= 30
       0 2011.71     9.2  2012.2    18.4  2012.2    27.7 2010.24    36.9 2006.82
    55.4 1997.99    73.8 1988.67    83.7  1984.6    93.6 1981.77   103.5 1980.09
   123.2 1977.15   133.1  1976.4   141.5 1976.72   156.5  1978.2   202.3 1982.88
   212.2 1983.78   222.1 1984.36     232 1984.02   251.7 1982.27   261.6 1981.69
   271.5 1981.47   281.4 1981.47   320.9 1982.91   340.7 1983.14   350.6 1984.73
   390.1 1996.42   409.9 2001.79   419.8 2004.06   429.7    2006   479.1 2015.35
#Mann= 3 , 0 , 0
       0      .1       0   141.5    .045       0   156.5      .1       0
#XS Ineff= 2 , 0
                          223.43         1986.56
Permanent Ineff=
       F       F
Bank Sta=141.5,156.5
XS Rating Curve= 0 ,0
Exp/Cntr=0.3,0.1

Type RM Length L Ch R = 1 ,14504.3 ,214.7,212.4,210.1
XS GIS Cut Line= 3
     1991155.242      385701.127     1991555.588      385553.755
     1991746.521      385443.986
#Sta/Elev= 30
       0 2010.63     9.9 2007.73    19.8 2006.49    29.8 2006.31    59.5 2008.16
    69.4  2008.1    79.4 2006.34   109.1  1995.6   138.9 1978.22   148.8 1975.15
   158.7 1974.75   218.3 1979.18   238.1 1979.09     248  1978.3   274.8  1971.3
   287.7 1970.54   289.8 1970.85   327.4 1976.95   406.8 1977.37   416.7 1978.09
   426.6 1980.62   436.6 1985.17   476.7 2007.01   496.7 2016.77   506.7  2019.6
   536.7 2018.45   546.7 2021.13   576.8 2033.03   596.8 2041.99   646.8  2067.5
#Mann= 3 , 0 , 0
       0      .1       0   274.8    .045       0   289.8      .1       0
Bank Sta=274.8,289.8
XS Rating Curve= 0 ,0
Exp/Cntr=0.3,0.1

Type RM Length L Ch R = 1 ,14292.3 ,362.9,368.8,374.6
XS GIS Cut Line= 3
     1991073.887      385874.007     1991333.933      385879.818
     1992020.123      385547.179
#Sta/Elev= 30
       0 2030.81      70 2024.03   130.1 2011.05   200.1 1992.27   220.1 1985.55
   250.1  1973.6     270 1968.88   299.7 1966.47   349.2 1965.71   471.9 1966.75
   486.9 1967.63   517.6 1973.67   527.5  1974.7     577 1975.98   586.9 1976.58
   596.8 1978.49   666.2 2007.01   676.1 2009.11   695.9 2008.99   705.8 2011.55
   735.5 2028.12   824.6 2068.48   834.5 2071.28   854.3 2072.65   864.2 2074.32
   893.9 2084.77   943.4  2097.3     993 2113.08  1002.9 2115.08  1022.7 2114.45
#Mann= 3 , 0 , 0
       0      .1       0   471.9    .045       0   486.9      .1       0
Bank Sta=471.9,486.9
XS Rating Curve= 0 ,0
Exp/Cntr=0.3,0.1

Type RM Length L Ch R = 1 ,13923.4 ,812.7,808.1,803.5
XS GIS Cut Line= 3
     1991016.175      386057.099     1991374.611      386158.751
     1991986.229      386038.171
#Sta/Elev= 30
       0 2028.99     9.8 2026.75      49 2015.54    78.4 2008.77   107.8 2003.42
   137.3    1999   186.3 1990.74   196.1 1989.53   215.7 1987.54   264.7  1983.7
   294.1 1980.76   333.4  1975.7   372.6 1969.93   412.2 1964.91     422 1964.31
   566.6 1961.06   570.5 1961.04   581.6 1961.32     620 1964.59   728.8 1972.46
   768.4  1976.1   778.3 1977.99   788.2 1980.94   837.6 2000.32   847.5 2003.12
   867.3 2004.68   877.2 2006.95     897 2014.16   906.9 2015.79     996 2023.83
#Mann= 3 , 0 , 0
       0      .1       0   566.6    .045       0   581.6      .1       0
Bank Sta=566.6,581.6
XS Rating Curve= 0 ,0
Exp/Cntr=0.3,0.1

Type RM Length L Ch R = 1 ,13114.9 ,340.1,344.6,349.1
XS GIS Cut Line= 3
     1991432.722      386874.969     1991586.716      386797.972
     1992063.226      386582.961
#Sta/Elev= 30
       0 2031.23    28.7 2017.73    47.8 2009.27    76.5 1997.87   124.4 1979.62
   143.5 1971.94   172.2 1959.85     182 1956.97   191.9  1955.9   201.8 1955.89
   260.9 1957.02   270.8 1957.11   290.5 1956.82     330 1955.04   360.5 1953.02
   375.5 1952.74   389.2 1952.42     399 1951.91   458.2 1948.17   468.1 1947.68
   477.9 1947.89   487.8 1949.45   497.7 1952.16   527.3 1961.08   537.1 1963.71
     547 1965.57   556.8 1966.78   606.2 1971.62   635.8  1974.7   694.9 1981.23
#Mann= 3 , 0 , 0
       0      .1       0   360.5    .045       0   375.5      .1       0
Bank Sta=360.5,375.5
XS Rating Curve= 0 ,0
Exp/Cntr=0.3,0.1

Type RM Length L Ch R = 1 ,12770.3 ,294.6,296.4,298.2
XS GIS Cut Line= 3
     1991354.433      387156.043     1991974.607      387018.794
     1992397.365      386841.555
#Sta/Elev= 30
       0 2117.88    29.8 2106.73     129  2066.7   168.7 2048.32   248.1 2009.77
     258 2005.64   307.7 1988.18   317.6 1983.61   357.3    1959   367.2  1954.8
   377.1 1953.23   533.2 1945.18   545.9 1945.05   548.2 1945.16   635.2 1949.88
   645.1  1950.9     685 1956.49   704.9 1958.14   734.8 1959.55   784.7 1958.95
   794.6 1959.14   814.6 1960.95   844.4 1964.63   864.4 1967.86   924.2 1981.83
   934.1 1983.85   944.1 1985.15     964 1986.59     974 1988.05  1093.6 2016.05
#Mann= 3 , 0 , 0
       0      .1       0   533.2    .045       0   548.2      .1       0
Bank Sta=533.2,548.2
XS Rating Curve= 0 ,0
Exp/Cntr=0.3,0.1

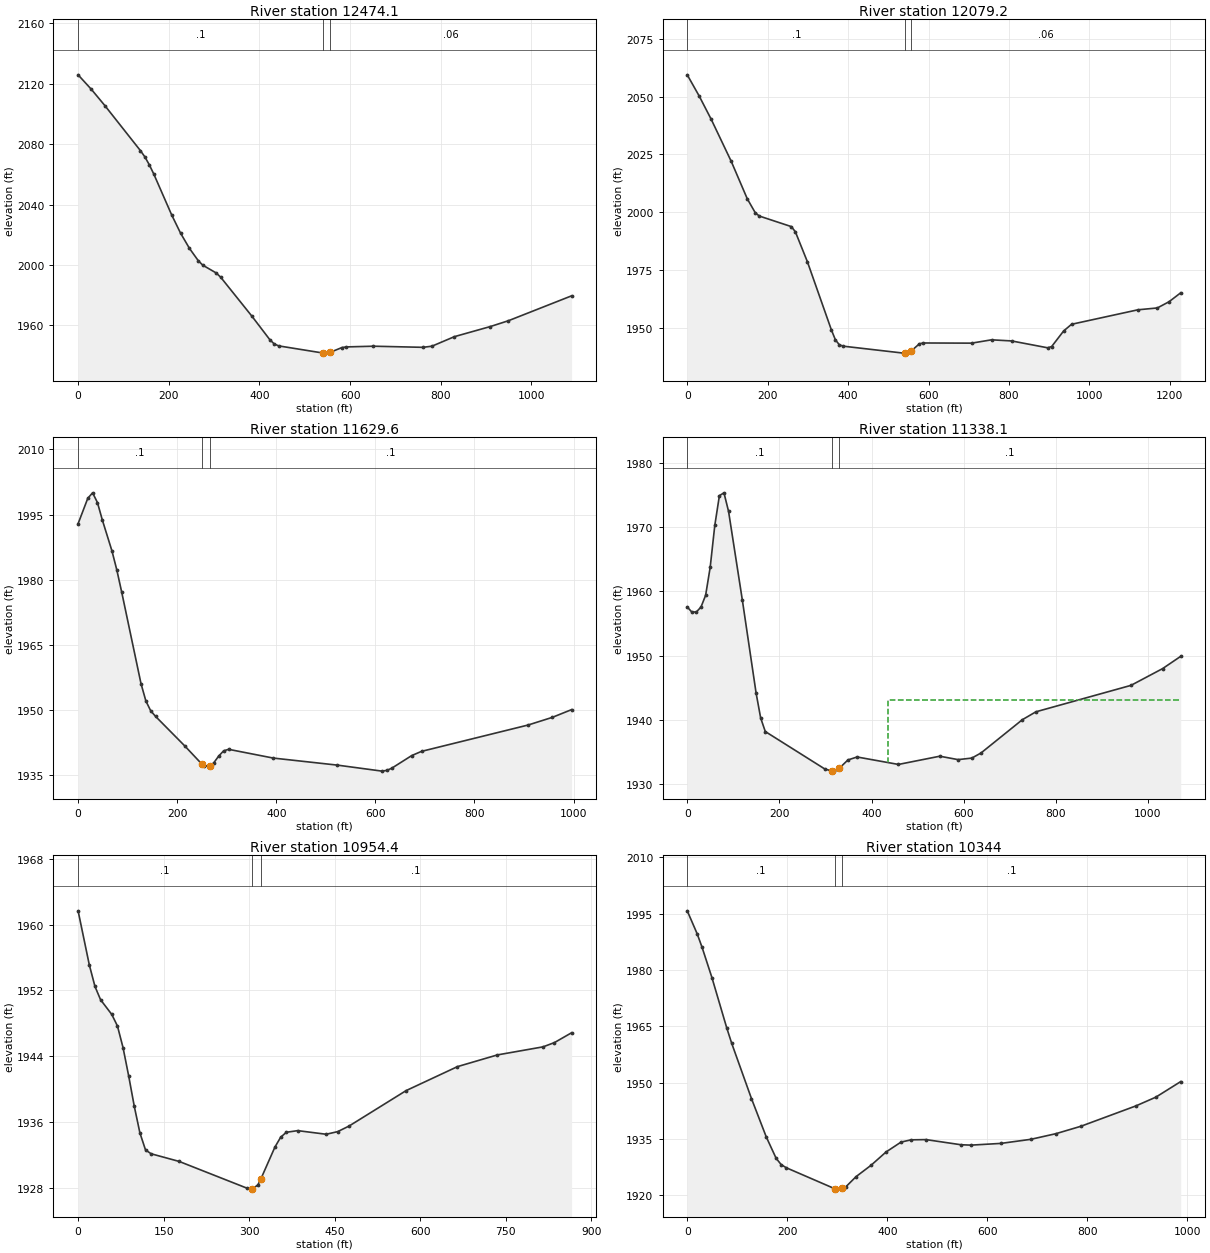
Type RM Length L Ch R = 1 ,12474.1 ,393.9,394.7,395.5
XS GIS Cut Line= 3
     1991341.783      387332.951     1991763.955      387351.479
     1992423.514      387259.955
#Sta/Elev= 30
       0 2125.87    29.5 2116.19      59 2105.53   137.6 2075.66   147.4 2071.52
   157.2 2066.26   167.1 2060.12   206.4 2033.16     226 2021.09   245.7 2010.98
   265.3 2002.77   275.2 1999.86   304.6 1994.74   314.5 1991.92   383.3 1966.16
   422.6 1950.69   432.5 1947.79   442.5 1946.47   540.4 1941.73   541.8 1941.68
   555.4 1942.14   581.6 1945.33   591.5 1945.79   651.2 1946.26   760.5 1945.52
   780.4 1946.26   830.1 1952.59   909.6  1959.3   949.3 1963.14  1088.5  1979.6
#Mann= 3 , 0 , 0
       0      .1       0   540.4    .045       0   555.4     .06       0
Bank Sta=540.4,555.4
XS Rating Curve= 0 ,0
Exp/Cntr=0.3,0.1

Type RM Length L Ch R = 1 ,12079.2 ,450.4,449.7,448.5
XS GIS Cut Line= 3
     1991374.197       387782.74     1992314.847      387684.027
     1992561.528      387549.057
#Sta/Elev= 30
       0 2059.47    29.9 2050.23    59.7 2040.18   109.5 2021.97   149.3  2005.8
   169.2 1999.76   179.2 1998.35   258.8 1993.78   268.8 1991.55   298.7 1978.59
   358.4 1949.07   368.4 1944.77   378.3  1942.6   388.3 1942.02   537.6 1939.02
   542.2 1939.03   557.2 1939.99   577.4 1943.09   587.4 1943.41   706.9 1943.34
   756.6 1944.78   806.4  1944.3     896 1941.33     906 1941.86   935.9 1948.62
   955.5  1951.5  1120.4 1957.77  1168.8 1958.57  1197.9 1961.26    1227 1965.14
#Mann= 3 , 0 , 0
       0      .1       0   542.2    .045       0   557.2     .06       0
Bank Sta=542.2,557.2
XS Rating Curve= 0 ,0
Exp/Cntr=0.3,0.1

Type RM Length L Ch R = 1 ,11629.6 ,300.9,291.5,282.9
XS GIS Cut Line= 4
      1991672.43      388204.258     1991933.828      388168.169
      1992347.97      388101.111     1992519.398      387839.612
#Sta/Elev= 30
       0  1992.9    19.6 1998.76    29.3 2000.01    39.1 1997.76    48.9 1993.77
    68.4 1986.62    78.2 1982.24      88 1977.16     127 1956.08   136.8  1952.1
   146.6 1949.82   156.4 1948.54     215 1941.78   250.3  1937.5   254.1 1937.14
   265.3  1937.1   273.9 1937.86   283.9 1939.42   293.8 1940.61   303.8 1940.96
   393.7 1938.95   523.6 1937.32   613.5 1935.94   623.5 1936.12   633.5 1936.64
   673.4 1939.52   693.2 1940.49   908.2 1946.55     957 1948.31   996.1  1950.1
#Mann= 3 , 0 , 0
       0      .1       0   250.3    .045       0   265.3      .1       0
#XS Ineff= 2 , 0
                           303.8         1940.96
Permanent Ineff=
       F       F
Bank Sta=250.3,265.3
XS Rating Curve= 0 ,0
Exp/Cntr=0.3,0.1

Type RM Length L Ch R = 1 ,11338.1 ,397,383.6,369.3
XS GIS Cut Line= 3
      1991803.18      388615.394     1992375.573      388166.486
     1992593.489      387900.628
#Sta/Elev= 30
       0 1957.58      10 1956.78    19.9  1956.8    29.9 1957.57    39.9 1959.39
    49.8 1963.74    59.8 1970.26    69.8 1974.89    79.7 1975.33    89.7 1972.44
   119.6 1958.65   149.5 1944.17   159.4  1940.3   169.4  1938.2   298.9 1932.36
   315.1 1932.05   318.9 1932.04   330.1 1932.49   348.8 1933.78   368.7 1934.24
   458.4 1933.08   548.1 1934.36   587.9 1933.83   617.8 1934.07   637.8 1934.87
   727.4 1940.04   756.9 1941.27   963.2 1945.38  1031.9 1947.99  1071.2  1949.9
#Mann= 3 , 0 , 0
       0      .1       0   315.1    .045       0   330.1      .1       0
#XS Ineff= 2 , 0
                          436.03         1943.13
Permanent Ineff=
       F       F
Bank Sta=315.1,330.1
XS Rating Curve= 0 ,0
Exp/Cntr=0.3,0.1

Type RM Length L Ch R = 1 ,10954.4 ,614.6,610.2,606.3
XS GIS Cut Line= 3
     1992294.217      388808.613     1992427.873      388512.247
     1992631.437      388011.909
#Sta/Elev= 30
       0 1961.66    19.7 1955.09    29.6 1952.48    39.4 1950.87    59.1 1949.08
      69 1947.68    78.8 1945.06    88.7 1941.62    98.5 1937.94   108.4  1934.7
   118.2 1932.64   128.1 1932.17   177.3 1931.24   295.6 1928.01   305.3 1927.88
   315.3  1928.4   320.3 1929.09   345.1 1932.98   355.1 1934.17   365.1 1934.78
   385.1 1934.98   435.1 1934.54   455.2 1934.86   475.2 1935.54   575.2 1939.84
   665.2 1942.75   735.2 1944.17   815.3 1945.15   835.3 1945.67   865.3 1946.86
#Mann= 3 , 0 , 0
       0      .1       0   305.3    .045       0   320.3      .1       0
Bank Sta=305.3,320.3
XS Rating Curve= 0 ,0
Exp/Cntr=0.3,0.1

Type RM Length L Ch R = 1 ,10344   ,440.7,441.5,441.5
XS GIS Cut Line= 3
     1992671.939       389100.62     1992776.539      388956.796
     1992949.419      388166.486
#Sta/Elev= 30
       0 1995.75    19.8 1989.65    29.6 1986.05    49.4 1977.95      79 1964.56
    88.9 1960.46   128.4 1945.75   158.1  1935.5   177.8 1929.82   187.8 1928.16
   197.8 1927.33   295.3 1921.71   297.7 1921.62   310.3 1921.82   317.7 1922.31
   337.6 1924.95   367.6 1927.98   397.6 1931.52   427.5 1934.15   447.5 1934.75
   477.5 1934.81   547.4 1933.44   567.4 1933.34   627.3  1933.8   687.2 1934.89
   737.2 1936.39   787.1 1938.36     897 1943.78   936.9 1946.11   986.8 1950.27
#Mann= 3 , 0 , 0
       0      .1       0   295.3    .045       0   310.3      .1       0
Bank Sta=295.3,310.3
XS Rating Curve= 0 ,0
Exp/Cntr=0.3,0.1

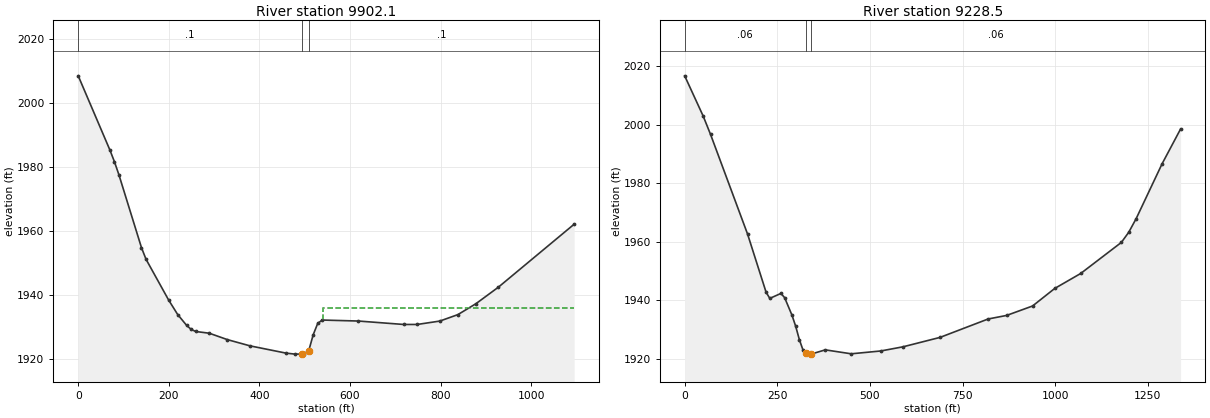
Type RM Length L Ch R = 1 ,9902.1  ,677.7,672.7,667.4
XS GIS Cut Line= 3
     1993057.409      389332.338     1993216.452      388448.391
     1993305.349      388272.781
#Sta/Elev= 30
       0 2008.55    69.9 1985.36    79.8 1981.75    89.8 1977.63   139.7  1954.8
   149.7 1951.18   199.6 1938.43   219.6 1933.89   239.5 1930.47   249.5 1929.22
   259.5 1928.58   289.4 1928.04   329.3 1926.04   379.2 1924.09     459 1921.81
     479  1921.5   494.1 1921.53     499 1921.56   509.1 1922.62   518.9 1927.58
   528.9 1931.14   538.9 1932.16   618.7 1931.85   718.5 1930.78   748.4 1930.78
   798.4 1931.84   838.3 1933.86   878.2 1937.28   927.7 1942.44    1095 1962.14
#Mann= 3 , 0 , 0
       0      .1       0   494.1    .045       0   509.1      .1       0
#XS Ineff= 2 , 0
                          539.39         1935.97
Permanent Ineff=
       F       F
Bank Sta=494.1,509.1
XS Rating Curve= 0 ,0
Exp/Cntr=0.3,0.1

Type RM Length L Ch R = 1 ,9228.5  ,791.3,811.2,831.4
XS GIS Cut Line= 3
     1993652.078      389491.175     1993626.847      388532.396
     1993530.045      388165.275
#Sta/Elev= 30
       0 2016.64      50 2002.87    69.9 1996.59   169.8 1962.54   219.8 1942.67
   229.8 1940.57   259.8 1942.27   269.8 1940.83   289.7 1934.82   299.7 1931.02
   309.7 1926.42   319.7 1922.82   327.2 1921.88   339.7 1921.52   342.2 1921.57
   379.6 1922.98   449.6 1921.63   529.5  1922.6   589.4 1924.02   689.4 1927.24
   819.2 1933.53   869.2 1934.75   939.1 1937.97   999.1 1943.98    1069 1949.08
  1178.9 1959.71  1198.9  1963.2  1218.9 1967.86  1288.8 1986.58  1338.8 1998.49
#Mann= 3 , 0 , 0
       0     .06       0   327.2    .045       0   342.2     .06       0
Bank Sta=327.2,342.2
XS Rating Curve= 0 ,0
Exp/Cntr=0.3,0.1