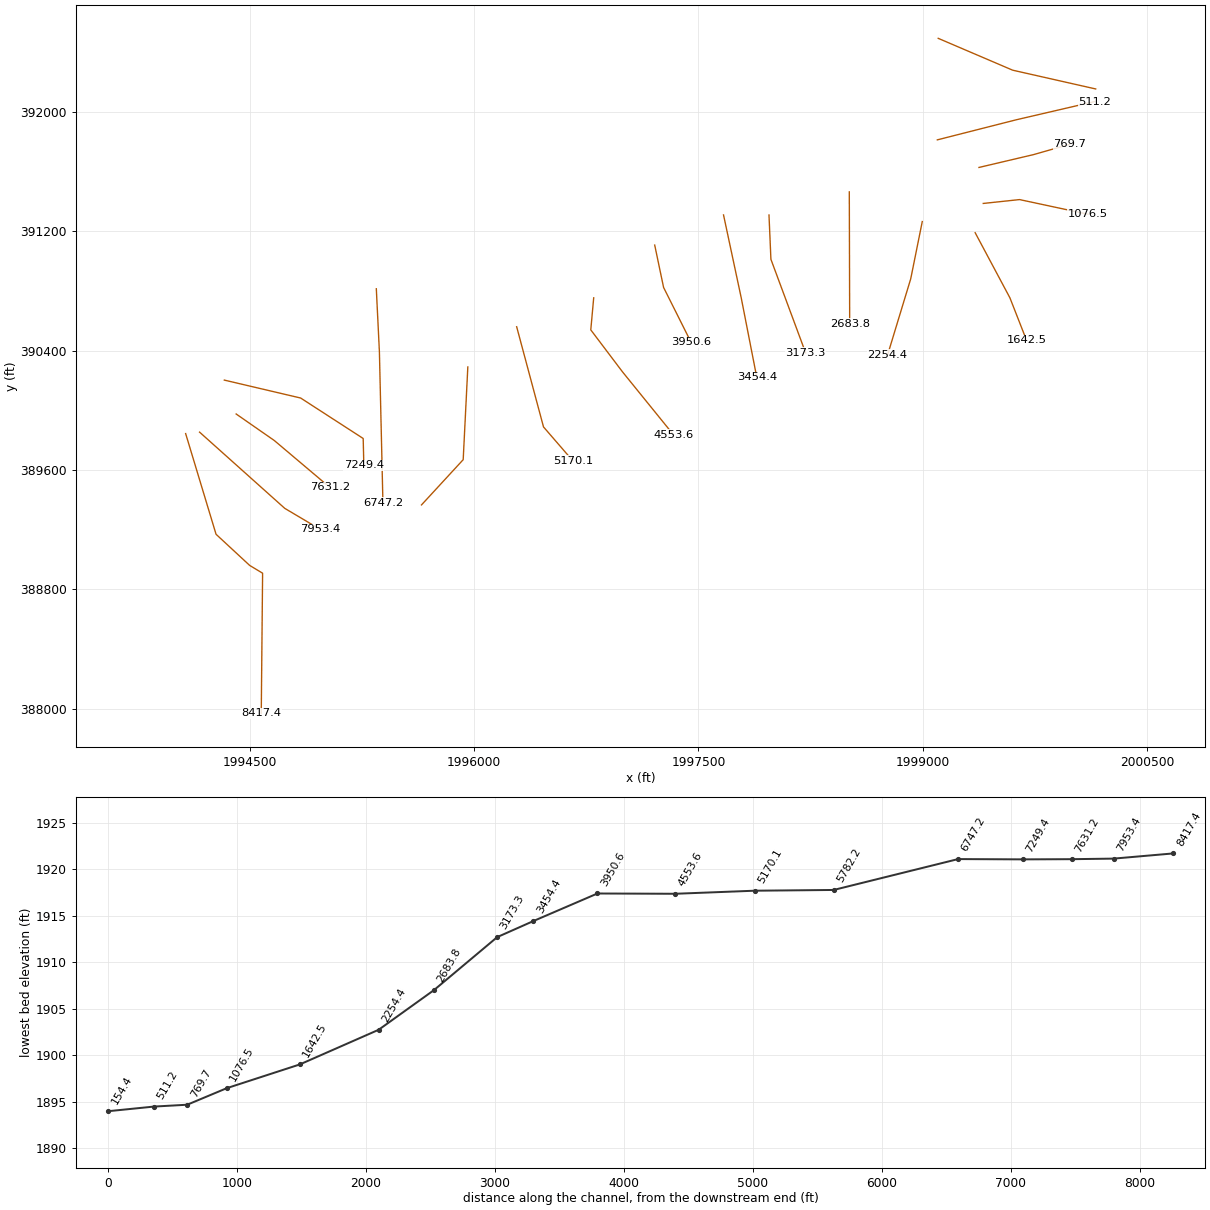
HEC-RAS study BrakensCrk.prj: BrakensCrk

--- BrakensCrk.g01 (geometry) --- (continued)

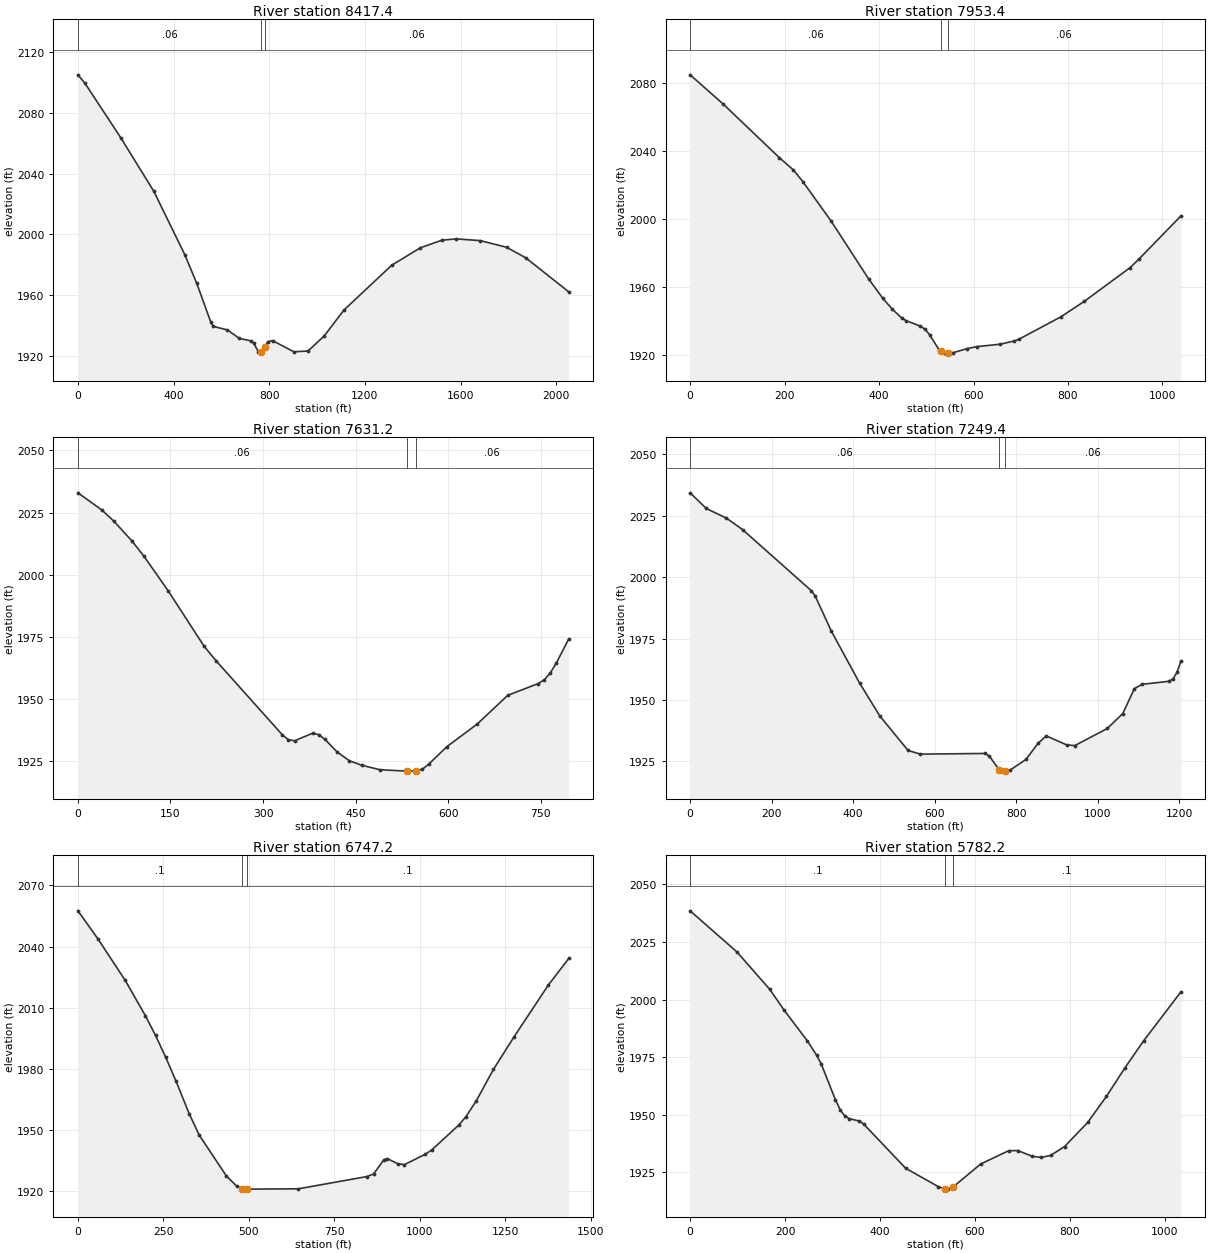
Type RM Length L Ch R = 1 ,8417.4  ,463.5,463.9,464.3
XS GIS Cut Line= 5
     1994070.251      389844.374      1994273.61      389169.513
     1994498.561       388960.75     1994585.054      388908.609
     1994576.043      387968.989
#Sta/Elev= 30
       0 2105.21    29.8 2099.54   178.7 2063.81   317.7  2028.3   446.7 1986.66
   496.4 1967.92   555.9 1942.01   565.8 1939.38   625.4 1936.96     675 1931.41
   724.6 1929.76   734.5 1928.46   754.3 1922.68   764.2  1921.7   767.4 1922.23
   782.4 1926.02   793.9 1929.16   813.7 1929.97   902.8 1922.59   962.2 1923.09
  1030.1 1933.06  1112.7 1950.16  1312.6  1979.7  1432.6  1991.2  1522.6 1996.18
  1582.6 1997.03  1682.5 1995.88  1792.5 1991.52  1872.4  1984.6  2052.4 1962.15
#Mann= 3 , 0 , 0
       0     .06       0   767.4    .045       0   782.4     .06       0
Bank Sta=767.4,782.4
XS Rating Curve= 0 ,0
Exp/Cntr=0.3,0.1

Type RM Length L Ch R = 1 ,7953.4  ,319.2,322.1,323.7
XS GIS Cut Line= 3
     1994163.361      389854.178     1994733.588      389342.992
     1994968.615      389203.525
#Sta/Elev= 30
       0  2084.9    69.6 2067.79     189 2036.15   218.8 2028.89   238.7 2022.04
   298.4 1998.89   377.9 1964.84   407.8 1953.42   427.7 1947.12   447.6 1941.86
   457.5 1940.23   487.3 1937.03   497.3 1935.25   507.2 1931.92   527.1 1923.06
   530.4 1922.51   537.1 1921.39   545.4 1921.18     547 1921.14     557 1921.41
   586.8 1923.81   606.7 1924.95   656.4 1926.38   686.2 1928.28   696.2 1929.32
   785.3 1942.55   834.1 1951.52   931.7 1971.47   951.3 1976.74  1039.1 2001.86
#Mann= 3 , 0 , 0
       0     .06       0   530.4    .045       0   545.4     .06       0
Bank Sta=530.4,545.4
XS Rating Curve= 0 ,0
Exp/Cntr=0.3,0.1

Type RM Length L Ch R = 1 ,7631.2  ,381.2,381.8,383.7
XS GIS Cut Line= 3
     1994408.167      389975.756     1994663.855      389797.549
     1995033.183      389485.041
#Sta/Elev= 30
       0 2032.93      39 2025.98    58.4 2021.49    87.7 2013.53   107.1 2007.41
   146.1 1993.61   204.5 1971.26     224  1965.4   331.4 1935.65   341.3 1933.69
   351.2 1933.27   380.8 1936.35   390.6 1935.73   400.5 1933.82   420.3 1928.76
     440 1925.24   459.8 1923.47   489.4 1921.64   532.7 1921.09   547.7 1921.08
   558.5 1921.89   568.4 1923.83     598 1930.91   647.4 1940.04   696.7 1951.54
   746.1 1956.28     756 1957.79   765.8 1960.58   775.7 1964.64   795.5 1974.18
#Mann= 3 , 0 , 0
       0     .06       0   532.7    .045       0   547.7     .06       0
Bank Sta=532.7,547.7
XS Rating Curve= 0 ,0
Exp/Cntr=0.3,0.1

Type RM Length L Ch R = 1 ,7249.4  ,524.5,502,478.1
XS GIS Cut Line= 4
     1994328.963      390202.873     1994839.479      390082.777
     1995257.878      389811.592     1995262.183      389631.233
#Sta/Elev= 30
       0 2034.37    39.6    2028    89.1 2024.06   128.6  2019.4   296.9 1994.57
   306.8 1992.33   346.3 1978.06   415.6 1956.92   465.1 1943.53   534.4 1929.48
   564.3 1927.99   723.9 1928.25   733.9 1927.16   757.9 1921.57   763.8 1921.06
   772.9  1921.1   783.7 1921.36   823.6 1925.81   853.5 1932.47   873.5 1935.39
   923.3 1931.75   943.3 1931.46    1023 1938.42    1061 1944.49  1089.5 1954.64
  1108.5 1956.41    1175 1957.65  1184.5 1958.68    1194  1961.3  1203.5 1965.76
#Mann= 3 , 0 , 0
       0     .06       0   757.9    .045       0   772.9     .06       0
Bank Sta=757.9,772.9
XS Rating Curve= 0 ,0
Exp/Cntr=0.3,0.1

Type RM Length L Ch R = 1 ,6747.2  ,966.2,964.9,965.1
XS GIS Cut Line= 3
     1995345.691      390815.137     1995366.352      390391.572
     1995389.896        389380.9
#Sta/Elev= 30
       0 2057.55    59.2 2043.61   138.1 2023.47   197.2 2006.14   226.8 1996.48
   256.4 1985.82     286 1974.35   325.4 1958.01     355 1947.47   434.1 1927.53
   464.1 1922.57   479.5  1921.3   494.1 1921.09   494.5 1921.09   644.3 1921.24
   844.5 1927.24   864.5 1928.54   894.5 1935.45   904.5  1936.1   934.6 1933.57
   954.6 1933.11  1014.6 1938.09  1034.6  1940.3  1114.7 1952.68  1134.7 1956.66
  1164.8  1964.4  1214.8 1979.76  1274.9 1995.69    1375 2021.03    1435 2034.18
#Mann= 3 , 0 , 0
       0      .1       0   479.5    .045       0   494.5      .1       0
Bank Sta=479.5,494.5
XS Rating Curve= 0 ,0
Exp/Cntr=0.3,0.1

Type RM Length L Ch R = 1 ,5782.2  ,604.9,611.9,619
XS GIS Cut Line= 3
     1995957.793      390290.847     1995926.801      389669.543
     1995647.868      389366.236
#Sta/Elev= 30
       0 2038.46    98.7 2020.61   167.9 2004.37   197.5 1995.53   246.9 1982.08
   266.6 1975.85   276.5 1971.92   306.1 1956.56     316 1952.25   325.8 1949.49
   335.7  1948.3   355.5 1947.34   365.4 1946.04   454.2 1926.81   523.3 1918.82
     538 1917.86   543.1 1917.77     553 1918.52   612.2 1928.66   671.1 1934.42
   690.8  1934.5   720.2 1932.04   739.8 1931.53   759.4 1932.38   788.9 1936.21
   837.9 1946.74   877.2 1957.98   916.4 1970.44   955.6 1982.08  1034.1  2003.3
#Mann= 3 , 0 , 0
       0      .1       0     538    .045       0     553      .1       0
Bank Sta=538,553
XS Rating Curve= 0 ,0
Exp/Cntr=0.3,0.1

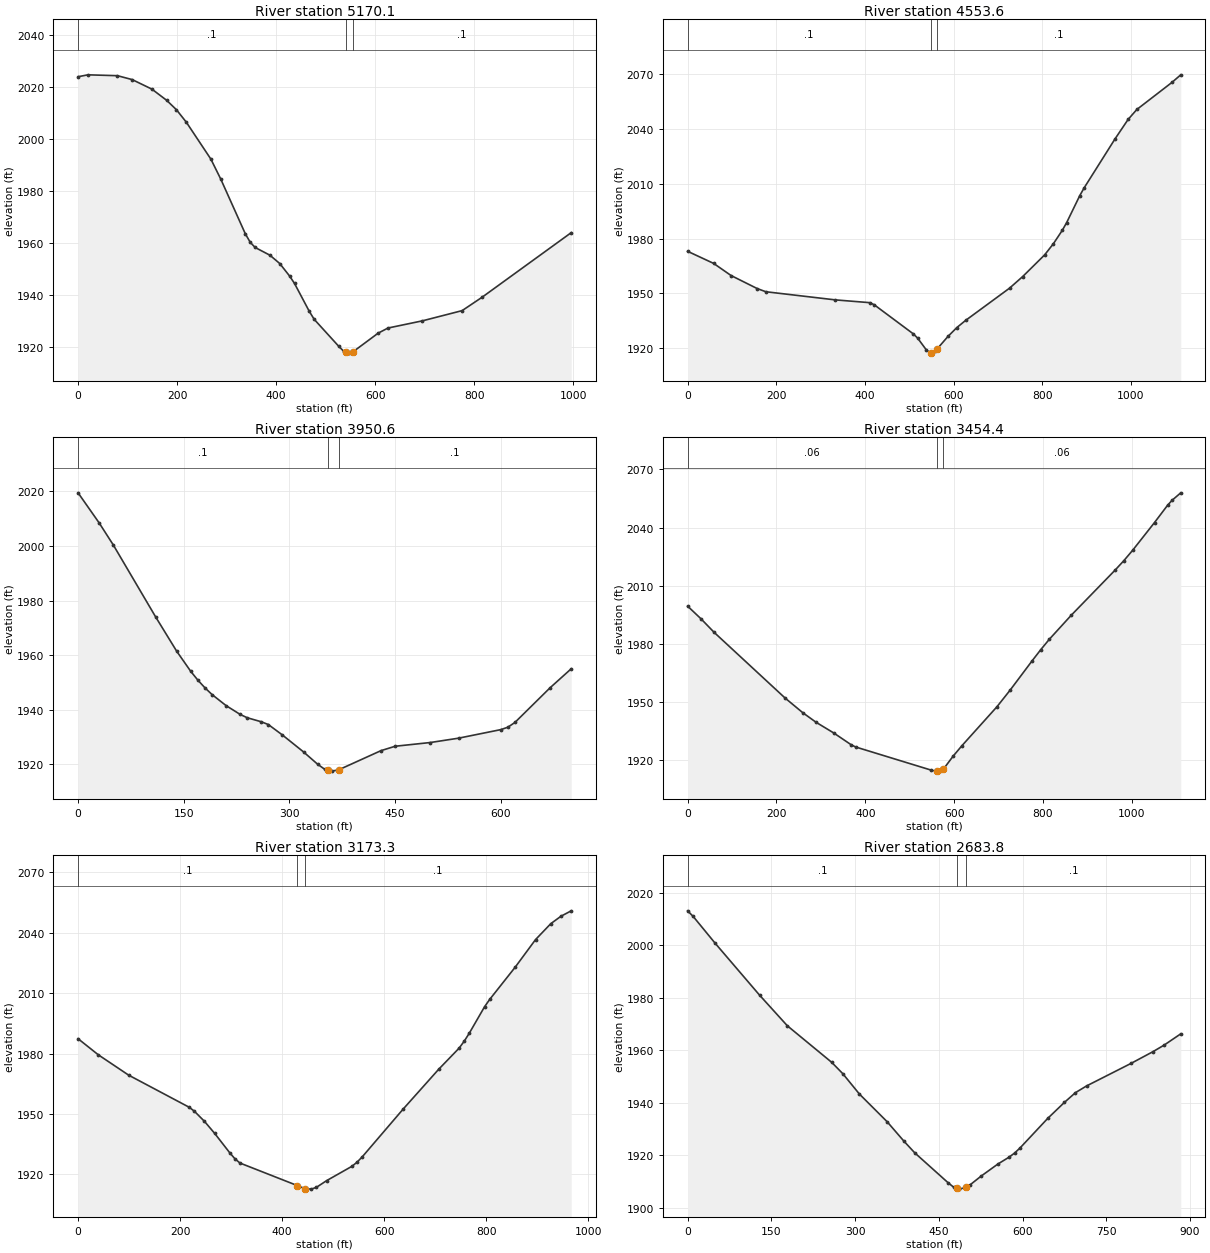
Type RM Length L Ch R = 1 ,5170.1  ,607.9,616.6,625.6
XS GIS Cut Line= 3
     1996284.426      390560.574     1996464.005      389889.074
     1996660.291      389661.795
#Sta/Elev= 30
       0 2023.82    19.9 2024.55    79.4 2024.22   109.2 2022.72     149 2019.06
   178.7 2014.78   198.6 2011.14   218.5 2006.36   268.1 1992.17     288 1984.52
   337.6 1963.51   347.6 1960.21   357.5 1958.25   387.3 1955.28   407.1 1952.09
     427 1947.28   436.9 1944.44   466.7 1933.73   476.6 1930.67   526.3 1920.28
   536.2  1918.4     540 1918.13   546.2 1917.69     555 1918.21   605.7 1925.36
   625.6 1927.33   695.1 1930.09   775.2 1934.01   815.2 1939.11   995.4 1963.95
#Mann= 3 , 0 , 0
       0      .1       0     540    .045       0     555      .1       0
Bank Sta=540,555
XS Rating Curve= 0 ,0
Exp/Cntr=0.3,0.1

Type RM Length L Ch R = 1 ,4553.6  ,607.1,603,598.5
XS GIS Cut Line= 4
     1996799.757      390754.282      1996780.26      390539.483
     1996992.379      390258.196     1997334.831      389834.639
#Sta/Elev= 30
       0 1973.03    58.8  1966.4      98 1959.79   156.9 1952.67   176.5 1950.92
   333.1 1946.47   411.4 1944.94   421.2 1943.77   509.3 1927.88     519 1925.57
   538.6 1919.13   548.4 1917.36   558.2 1918.44   563.4 1919.78   587.8 1926.58
   607.6 1931.36   627.4 1935.27   726.4 1952.88   756.2 1959.25   805.7  1971.1
   825.5 1977.23   845.3 1984.46   855.2 1988.68   884.9 2003.49   894.8 2007.74
   964.1 2034.37   993.8 2045.08  1013.6 2050.55  1092.9 2065.37  1112.7  2069.5
#Mann= 3 , 0 , 0
       0      .1       0   548.4    .045       0   563.4      .1       0
Bank Sta=548.4,563.4
XS Rating Curve= 0 ,0
Exp/Cntr=0.3,0.1

Type RM Length L Ch R = 1 ,3950.6  ,501.9,496.1,490
XS GIS Cut Line= 3
     1997207.825      391108.113     1997267.228      390824.015
       1997450.6       390457.27
#Sta/Elev= 30
       0 2019.51      30 2008.45      50 2000.39   110.1    1974   140.1 1961.37
   160.1 1953.97   170.1 1950.78   180.2 1947.95   190.2  1945.5   210.2 1941.43
   230.2  1938.2   240.2 1936.98   260.2  1935.5   270.2 1934.48   290.2 1930.65
   320.2 1924.43   340.2 1919.92   350.2 1918.08   354.9 1917.76   360.2 1917.39
   369.9 1917.85   430.2 1924.91   450.3 1926.52   500.3 1927.89   540.3 1929.48
   600.3 1932.62   610.3  1933.5   620.3 1935.24   670.3 1947.98   700.3 1954.95
#Mann= 3 , 0 , 0
       0      .1       0   354.9    .045       0   369.9      .1       0
Bank Sta=354.9,369.9
XS Rating Curve= 0 ,0
Exp/Cntr=0.3,0.1

Type RM Length L Ch R = 1 ,3454.4  ,277.8,281.1,284.7
XS GIS Cut Line= 3
     1997668.222      391309.986     1997786.618      390754.203
     1997890.429      390222.164
#Sta/Elev= 30
       0 1999.48    29.9    1993    59.8 1985.94   219.3 1952.14   259.2 1944.56
   289.1 1939.63     329  1934.1   368.9 1927.92   378.8 1926.84   548.3 1914.95
   558.3 1914.43   560.8 1914.48   568.2 1914.63   575.8 1915.77   578.1 1916.12
   597.8 1922.15   617.5 1927.51   696.4  1947.6     726 1956.14   775.2 1971.15
   794.9 1976.98   814.6 1982.45   863.9 1994.82   962.5 2018.05   982.2 2022.92
  1001.9 2028.24  1051.2 2042.56  1080.8 2051.52  1090.6    2054  1110.3 2057.88
#Mann= 3 , 0 , 0
       0     .06       0   560.8    .045       0   575.8     .06       0
Bank Sta=560.8,575.8
XS Rating Curve= 0 ,0
Exp/Cntr=0.3,0.1

Type RM Length L Ch R = 1 ,3173.3  ,497.5,489.6,481.6
XS GIS Cut Line= 3
     1997972.308      391309.565     1997985.221      391012.553
     1998217.665      390384.954
#Sta/Elev= 30
       0 1987.35    39.6 1979.38    99.1 1969.28     218 1953.31   227.9 1951.38
   247.7 1946.35   267.6 1940.41   297.3 1930.74   307.3  1927.8   317.3 1925.65
   429.7 1914.47   444.7 1912.97   457.1  1912.7   467.1 1913.58   487.1  1916.9
     537 1924.06     547 1926.12     557 1928.72   636.9 1952.35   706.8 1972.18
   746.8 1982.66   756.8  1986.1   766.8 1990.08   796.7  2003.2   806.7 2006.83
   856.7 2022.83   896.6 2036.53   926.6 2044.46   946.6 2048.16   966.6 2050.83
#Mann= 3 , 0 , 0
       0      .1       0   429.7    .045       0   444.7      .1       0
Bank Sta=429.7,444.7
XS Rating Curve= 0 ,0
Exp/Cntr=0.3,0.1

Type RM Length L Ch R = 1 ,2683.8  ,433.9,429.3,422.6
XS GIS Cut Line= 2
     1998509.512      391464.527     1998512.094       390581.24
#Sta/Elev= 30
       0 2013.16     9.9 2011.04    49.6 2000.73     129 1980.97   178.6 1969.32
     258 1955.39   277.9 1951.06   307.7 1943.28   357.3 1932.74   387.1 1925.39
   406.9 1920.84   466.5 1909.46   476.4 1907.77   483.2 1907.25   486.3 1907.01
   498.2 1907.65   506.2 1908.68     526 1912.02   555.8 1916.59   575.6 1919.18
   585.6 1920.75   595.5 1922.73   645.1 1934.01   674.9 1940.09   694.7 1943.81
   714.6 1946.37     794 1954.94   833.7 1959.46   853.5 1961.94   883.3 1966.24
#Mann= 3 , 0 , 0
       0      .1       0   483.2    .045       0   498.2      .1       0
Bank Sta=483.2,498.2
XS Rating Curve= 0 ,0
Exp/Cntr=0.3,0.1

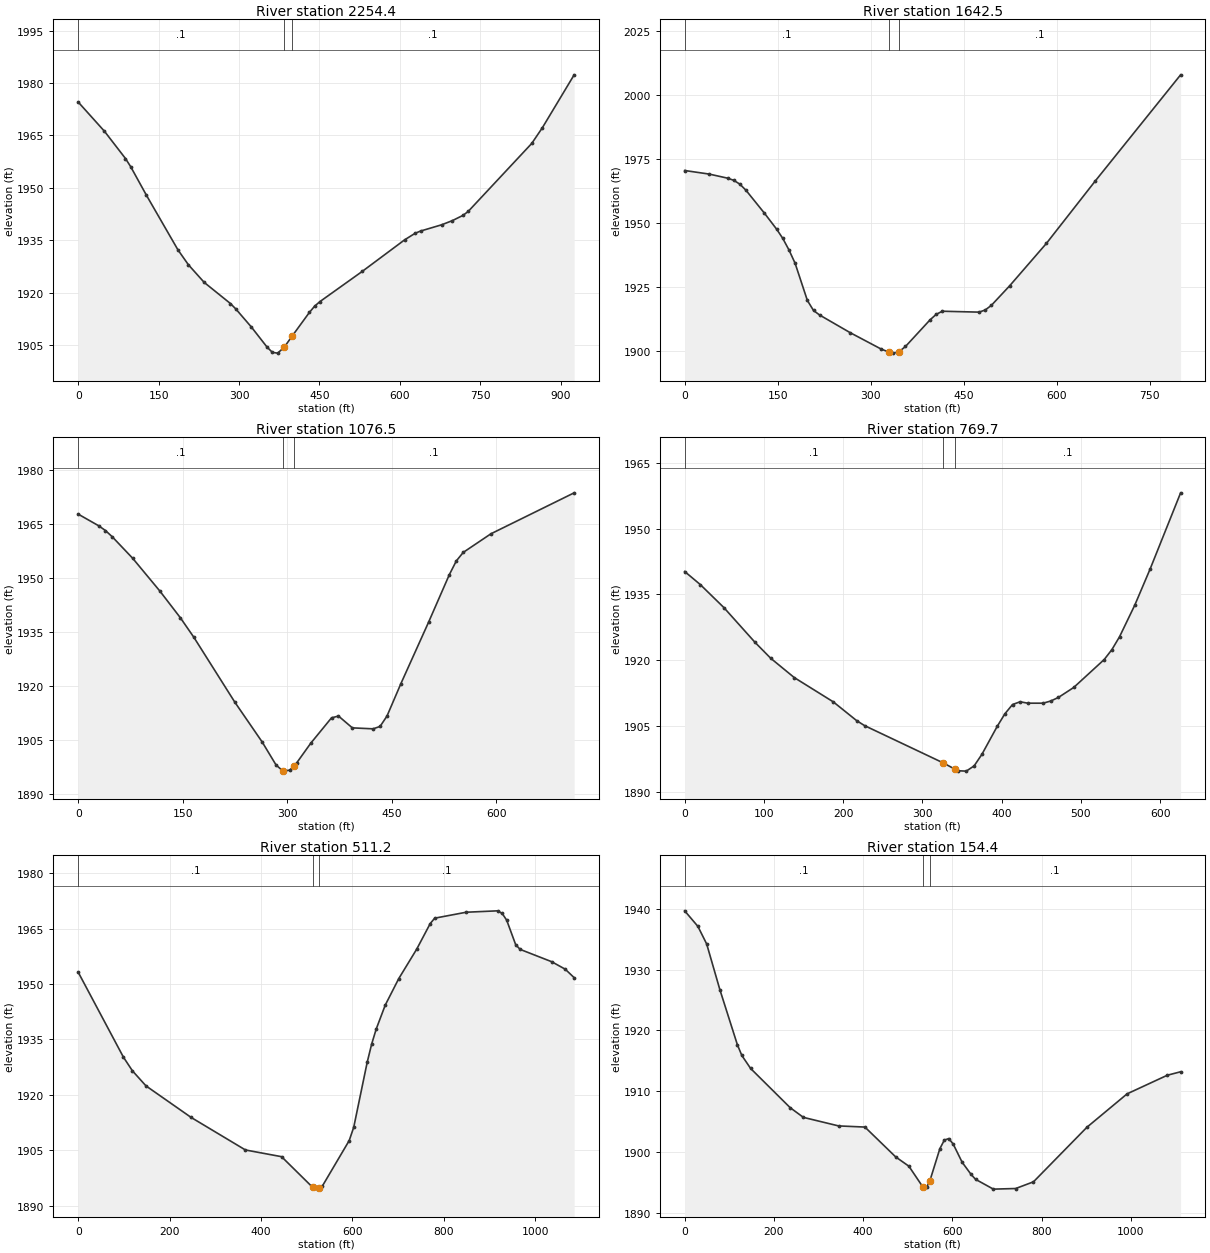
Type RM Length L Ch R = 1 ,2254.4  ,596.3,611.9,629.6
XS GIS Cut Line= 3
     1998997.644      391265.659     1998920.366      390881.565
     1998765.481      390370.979
#Sta/Elev= 30
       0 1974.56      49  1966.2    88.2 1958.41      98 1956.05   127.3  1947.9
   186.1 1932.28   205.7    1928   235.1 1922.97     284 1916.93   293.8 1915.42
   323.2 1910.19   352.6 1904.42   362.4 1902.95   372.2 1902.74   384.3 1904.41
   399.3 1907.64   431.3 1914.37   441.2 1916.18   451.1 1917.49   530.1 1926.13
   609.2 1935.16   628.9 1937.04   638.8 1937.66   678.3 1939.46   698.1 1940.64
   717.9 1942.14   727.7 1943.27   846.3 1962.73   866.1 1967.22   925.4 1982.35
#Mann= 3 , 0 , 0
       0      .1       0   384.3    .045       0   399.3      .1       0
Bank Sta=384.3,399.3
XS Rating Curve= 0 ,0
Exp/Cntr=0.3,0.1

Type RM Length L Ch R = 1 ,1642.5  ,546.4,566,585.7
XS GIS Cut Line= 3
     1999351.476       391190.76      1999583.92      390754.282
     1999694.976      390470.184
#Sta/Elev= 30
       0 1970.54    39.6 1969.14    69.2 1967.54    79.1  1966.7      89 1965.19
    98.9 1962.78   128.6 1953.82   148.4 1947.52   158.2 1943.93   168.1 1939.45
     178 1934.23   197.8 1919.65   207.7 1915.72   217.6 1913.93     267    1907
   316.5 1900.64   330.2 1899.31   336.3 1899.01   345.2  1899.5     356 1901.61
   395.6 1912.04   405.5 1914.19   415.4 1915.42   474.7 1915.07   484.6 1915.91
   494.5 1917.73     524 1925.39   583.1 1941.96   661.8 1966.38   799.6 2008.02
#Mann= 3 , 0 , 0
       0      .1       0   330.2    .045       0   345.2      .1       0
Bank Sta=330.2,345.2
XS Rating Curve= 0 ,0
Exp/Cntr=0.3,0.1

Type RM Length L Ch R = 1 ,1076.5  ,296.6,306.7,316.7
XS GIS Cut Line= 3
     1999405.712      391387.046     1999648.487      391412.873
     2000105.627       391314.73
#Sta/Elev= 30
       0 1967.74    29.3 1964.52    39.1 1963.19    48.8 1961.47    78.1 1955.51
   117.2  1946.4   146.5 1939.02     166 1933.57   224.6 1915.63     264 1904.54
   283.9 1898.17   293.9 1896.46     294 1896.46   303.8 1896.74     309 1897.82
   313.8 1898.82   333.7  1904.2   363.5 1911.24   373.5 1911.74   393.4 1908.46
   423.2 1908.19   433.2 1908.86   443.1 1911.73     463  1920.7   502.8 1937.77
   532.6 1950.96   542.6 1954.76   552.5 1957.12   592.3 1962.29   711.7 1973.65
#Mann= 3 , 0 , 0
       0      .1       0     294    .045       0     309      .1       0
Bank Sta=294,309
XS Rating Curve= 0 ,0
Exp/Cntr=0.3,0.1

Type RM Length L Ch R = 1 ,769.7   ,258.2,258.6,259
XS GIS Cut Line= 3
     1999376.996      391628.278     1999742.019      391714.368
     1999983.072      391783.241
#Sta/Elev= 30
       0 1940.22    19.7 1937.24    49.4    1932    88.8 1924.05   108.6 1920.42
   138.2 1916.03   187.5 1910.48   217.1 1906.18     227 1905.06   325.6 1896.61
   340.6 1895.16   345.4 1894.76   355.3 1894.68   365.2 1895.88     375 1898.51
   394.3 1904.89     404 1907.76   413.6 1909.87   423.2  1910.5   432.9 1910.18
   452.2 1910.18   461.8 1910.67   471.5 1911.49   490.8 1913.76   529.3 1920.14
     539  1922.4   548.6 1925.32   567.9 1932.56   587.2 1940.78   625.7 1958.17
#Mann= 3 , 0 , 0
       0      .1       0   325.6    .045       0   340.6      .1       0
Bank Sta=325.6,340.6
XS Rating Curve= 0 ,0
Exp/Cntr=0.3,0.1

Type RM Length L Ch R = 1 ,511.2   ,371.3,356.5,345.8
XS GIS Cut Line= 3
      1999098.37      391813.193     1999625.243      391947.494
      2000152.46      392070.285
#Sta/Elev= 30
       0 1953.18    98.9  1930.2   118.6  1926.5   148.3 1922.42   247.2 1913.87
   365.8 1905.08   444.9 1903.26   512.7 1894.99     524 1894.48   527.7 1894.77
   533.8 1895.24   592.9 1907.63   602.8 1911.24   632.3 1928.86   642.1 1933.79
     652 1937.82   671.7 1944.28   701.2 1951.44   740.6 1959.44   770.1 1966.35
   779.9 1967.81   848.8 1969.42   917.7  1969.8   927.6 1969.08   937.4 1967.27
   957.1 1960.63   966.9 1959.36  1035.8 1956.03  1065.4 1954.01    1085 1951.71
#Mann= 3 , 0 , 0
       0      .1       0   512.7    .045       0   527.7      .1       0
Bank Sta=512.7,527.7
XS Rating Curve= 0 ,0
Exp/Cntr=0.3,0.1

Type RM Length L Ch R = 1 ,154.4   ,156.4,154.4,148.3
XS GIS Cut Line= 3
     1999104.208      392493.726     1999602.256      392280.278
     2000157.641      392154.465
#Sta/Elev= 30
       0 1939.63    29.6 1937.08    49.3 1934.19    78.8 1926.71   118.2 1917.64
   128.1  1915.9   147.8 1913.77   236.4 1907.34     266 1905.75   344.8 1904.35
   403.9 1904.16   472.9 1899.26   502.4 1897.74   534.4 1894.26   541.9 1894.26
   549.4 1895.34   571.8 1900.61   581.8 1902.02   591.8 1902.27   601.8 1901.36
   621.8 1898.38   641.8 1896.39   651.8 1895.59   691.7 1893.98   741.7 1894.08
   781.6 1895.18   901.5 1904.14   991.4 1909.61  1081.4 1912.66  1111.3 1913.23
#Mann= 3 , 0 , 0
       0      .1       0   534.4    .045       0   549.4      .1       0
Bank Sta=534.4,549.4
XS Rating Curve= 0 ,0
Exp/Cntr=0.3,0.1

Chan Stop Cuts=-1
Use User Specified Reach Order=0
Composite Channel Slope=5